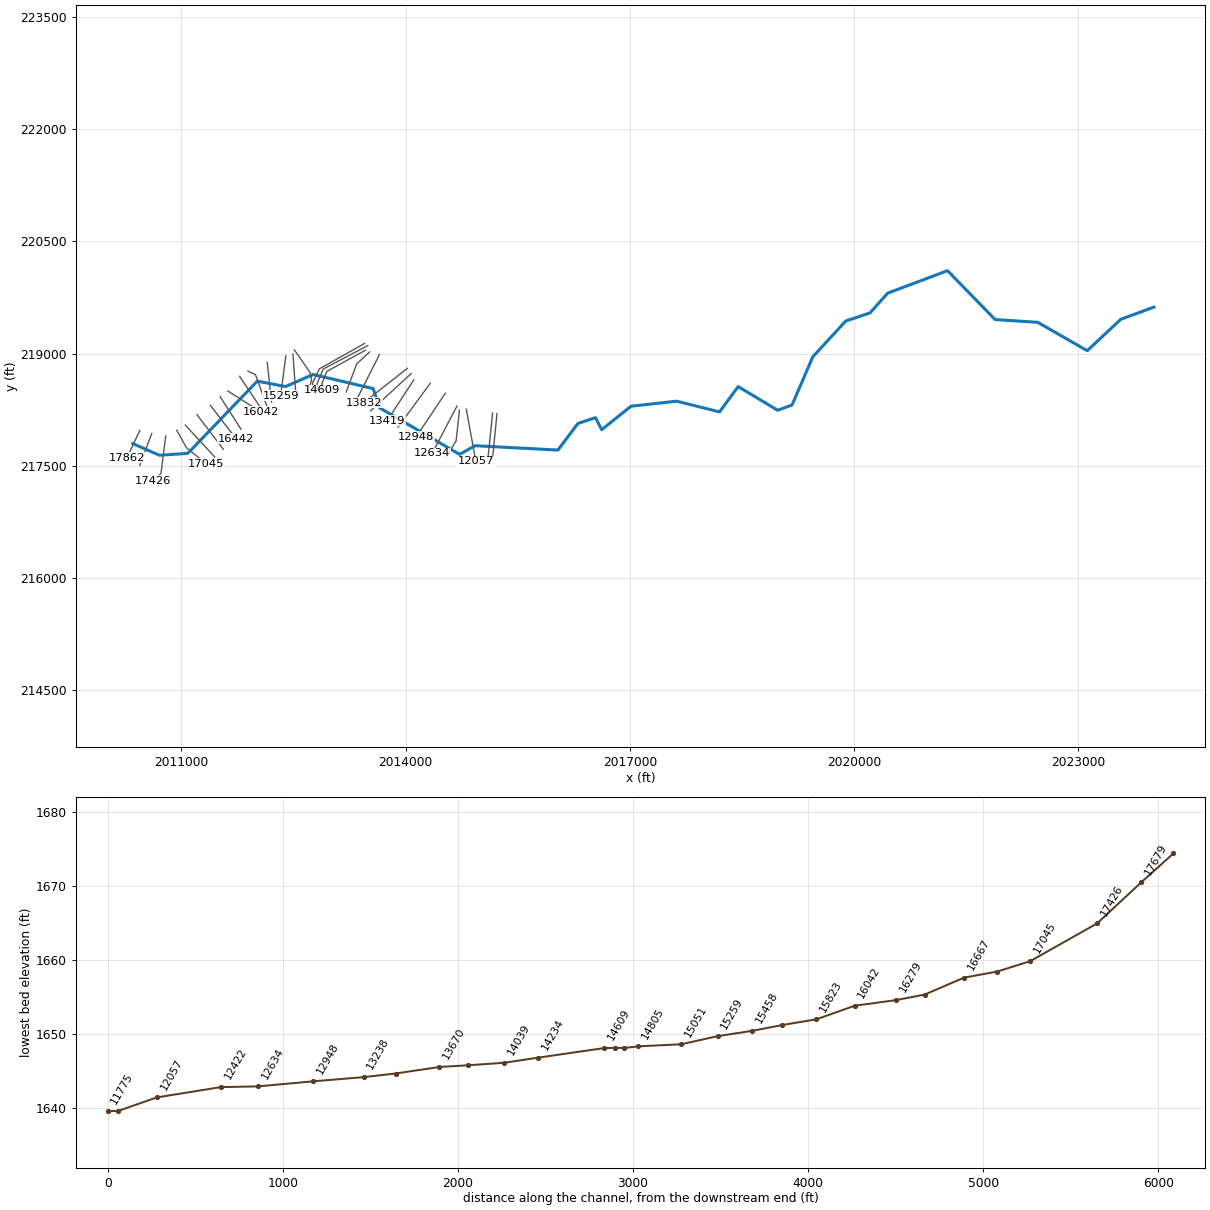
--- WOLFCK_A.prj (project) ---

Proj Title=WOLFCK_A
Current Plan=p01
Default Exp/Contr=0,0
English Units
Geom File=g01
Flow File=f01
Plan File=p01
BEGIN DESCRIPTION:
Stream Name: Wolf Creek
Flood Zone: Approximate
Summers County, West Virginia
HEC-RAS Version: 5.0.7
Hydrology Method:
regression
Model Notes:
KWSEL tie-in/shared XS with WOLFCK_AE, coincident peak with WOLFCK_T!
END DESCRIPTION:
DSS Export Rating Curves= 0
DSS Export Rating Curve Sorted= 0
DSS Export Volume Flow Curves= 0
DXF OffsetX= 0
DXF OffsetY= 0
DXF ScaleX= 0
DXF ScaleY= 0

--- WOLFCK_A.p01 (plan) ---

Plan Title=Floodplain
Program Version=5.07
Short Identifier=Floodplain
Geom File=g01
Flow File=f01
Subcritical Flow
K Sum by GR= 0
Std Step Tol= 0.01
Critical Tol= 0.01
Num of Std Step Trials= 20
Max Error Tol= 0.3
Flow Tol Ratio= 0.001
Split Flow NTrial= 30
Split Flow Tol= 0.02
Split Flow Ratio= 0.02
Log Output Level= 0
Friction Slope Method= 1
Unsteady Friction Slope Method= 2
Unsteady Bridges Friction Slope Method= 1
Parabolic Critical Depth
Global Vel Dist= 0 , 0 , 0
Global Log Level= 0
CheckData=True
Encroach Param=-1 ,0,0, 0
Mapping Interval=1HOUR
Computation Time Step Use Courant=        0
Computation Time Step Use Time Series=    0
Computation Time Step Count To Double=0
Computation Time Step Max Doubling=0
Computation Time Step Max Halving=0
Computation Time Step Residence Courant=0
Run HTab= 0
Run UNet= 0
Run Sediment= 0
Run PostProcess= 0
Run WQNet= 0
Run RASMapper= 0
UNET Theta= 0
UNET Theta Warmup= 0
UNET ZTol= 0
UNET ZSATol= 0
UNET MxIter= 0
UNET Max Iter WO Improvement= 0
UNET MaxInSteps= 0
UNET DtIC= 0
UNET DtMin= 0
UNET MaxCRTS= 0
UNET WFStab= 0
UNET SFStab= 0
UNET WFX= 1
UNET SFX= 1
UNET 1D Methodology=Finite Difference
UNET DSS MLevel= 1
UNET Pardiso=0
UNET DZMax Abort= 0
UNET Use Existing IB Tables= 0
UNET Froude Reduction=False
UNET Froude Limit= 0
UNET Froude Power= 0
UNET D1 Cores= 0
UNET D2 Coriolis=0
UNET D2 Cores= 0
UNET D2 Theta= 1
UNET D2 Theta Warmup= 1
UNET D2 Z Tol= 0.01
UNET D2 Volume Tol= 0.01
UNET D2 Max Iterations= 20
UNET D2 Equation= 0
UNET D2 RampUpFraction=0.1
UNET D2 TimeSlices= 1
UNET D2 BCVolumeCheck=0
UNET D1D2 MaxIter= 0
UNET D1D2 ZTol=0.01
UNET D1D2 QTol=0.1
UNET D1D2 MinQTol=1
Write IC File= 0
Write IC File at Fixed DateTime=0
Write IC File at Sim End=0
Echo Input=False
Echo Parameters=False
Echo Output=False
Write Detailed= 0
HDF Write Warmup=0
HDF Write Time Slices=0
HDF Flush=0
HDF Face Node Velocities=0
HDF Compression= 1
HDF Chunk Size= 1
HDF Spatial Parts= 1
HDF Use Max Rows=0
HDF Fixed Rows= 1
Calibration Method= 0
Calibration Iterations= 20
Calibration Max Change=0.05
Calibration Tolerance=0.2
Calibration Maximum=1.5
Calibration Minimum=0.5
Calibration Optimization Method= 1
WQ AD Non Conservative
WQ ULTIMATE=-1
WQ Max Comp Step=1HOUR
WQ Output Interval=15MIN
WQ Output Selected Increments= 0
WQ Output face flow=0
WQ Output face velocity=0
WQ Output face area=0
WQ Output face dispersion=0
WQ Output cell volume=0
WQ Output cell surface area=0
WQ Output cell continuity=0
WQ Output cumulative cell continuity=0
WQ Output face conc=0
WQ Output face dconc_dx=0
WQ Output face courant=0
WQ Output face peclet=0
WQ Output face adv mass=0
WQ Output face disp mass=0
WQ Output cell mass=0
WQ Output cell source sink temp=0
WQ Output nsm pathways=0
WQ Output nsm derived pathways=0
WQ Output MaxMinRange=-1
WQ Daily Max Min Mean=-1
WQ Daily Range=0
WQ Daily Time=0
WQ Create Restart=0
WQ Fixed Restart=0
WQ System Summary=0
WQ Write To DSS=0
WQ Use Fixed Temperature=0
Sorting and Armoring Iterations= 10
XS Update Threshold= 0.02
Bed Roughness Predictor= 0
Hydraulics Update Threshold= 0.02
Energy Slope Method= 1
Volume Change Method= 1
Sediment Retention Method= 0
XS Weighting Method= 0
Number of US Weighted Cross Sections= 1
Number of DS Weighted Cross Sections= 1
Upstream XS Weight=0
Main XS Weight=1
Downstream XS Weight=0
Number of DS XS's Weighted with US Boundary= 1
Upstream Boundary Weight= 1
Weight of XSs Associated with US Boundary= 0
Number of US XS's Weighted with DS Boundary= 1
Downstream Boundary Weight= 0.5
Weight of XSs Associated with DS Boundary= 0.5
Percentile Method= 0
Sediment Output Level= 3
Mass or Volume Output= 0
Output Increment Type= 1
Profile and TS Output Increment= 1
XS Output Flag= 0
XS Output Increment= 10
Write Gradation File= 0
Read Gradation Hotstart= 0
Write HDF5 File= 1
Write Binary Output= 1
Write DSS Sediment File= 0
SV Curve= 0
Specific Gage Flag= 0

--- WOLFCK_A.f01 (steady flow) ---

Flow Title=Flows
Program Version=5.07
Number of Profiles= 6
Profile Names=01pct,10pct,04pct,02pct,0_2pct,01plus
River Rch & RM=WOLFCK_A,Main            ,17862
     372     193     259     313     523     550
River Rch & RM=WOLFCK_A,Main            ,17426
     826     443     585     702    1146    1222
River Rch & RM=WOLFCK_A,Main            ,14727
    1278     697     913    1090    1758    1890
River Rch & RM=WOLFCK_A,Main            ,12057
    1526     837    1093    1303    2092    2256
River Rch & RM=WOLFCK_A,Main            ,7042
    1801     995    1295    1540    2462    2663
River Rch & RM=WOLFCK_A,Main            ,3636
    2067    1148    1490    1769    2818    3056
River Rch & RM=WOLFCK_A,Main            ,0
    2097    1165    1513    1769    2859    3102
Boundary for River Rch & Prof#=WOLFCK_A,Main            , 1
Up Type= 0
Dn Type= 1
Dn Known WS=1444.4
Boundary for River Rch & Prof#=WOLFCK_A,Main            , 2
Up Type= 0
Dn Type= 1
Dn Known WS=1442.1
Boundary for River Rch & Prof#=WOLFCK_A,Main            , 3
Up Type= 0
Dn Type= 1
Dn Known WS=1443.3
Boundary for River Rch & Prof#=WOLFCK_A,Main            , 4
Up Type= 0
Dn Type= 1
Dn Known WS=1443.8
Boundary for River Rch & Prof#=WOLFCK_A,Main            , 5
Up Type= 0
Dn Type= 1
Dn Known WS=1445.2
Boundary for River Rch & Prof#=WOLFCK_A,Main            , 6
Up Type= 0
Dn Type= 1
Dn Known WS=1445.4
DSS Import GetInterval= 0
DSS Import GetPeak= 0
DSS Import FillOption= 0

--- WOLFCK_A.g01 (geometry) ---

Geom Title=Geometry
Program Version=5.07

River Reach=WOLFCK_A        ,Main
Reach XY= 30
2010351.50599999217795.1839997242010708.27699999217639.454999738
2011086.61799998217665.2679997432012016.54799998218631.132999736
2012394.67299998218558.7369997272012763.42299999218720.194999732
2013567.06899999218531.1329997112013651.05299998 218275.66399973
2014722.99699998217651.3119997352014929.93299999217767.383999726
2016038.63399999217709.1169997122016305.92399999218064.731999726
2016541.76699998218142.8839997432016623.61899999217981.029999739
2017017.15399998218295.9509997382017628.49699999218363.003999739
2018201.13199998218220.0769997412018450.23899999218558.282999729
2018978.88899998218241.8489997332019171.47172627218312.287273462
2019448.64899999218956.3689997372019889.62099998 219435.53599974
2020214.13199998219543.9319997232020451.43602508219809.092795808
2021251.42699998220109.1469997422021888.38163684219455.182820916
2022458.37099998219418.1749997212023120.38199998219038.723999727
2023570.17699998219459.1469997372024014.72644303219622.053536572

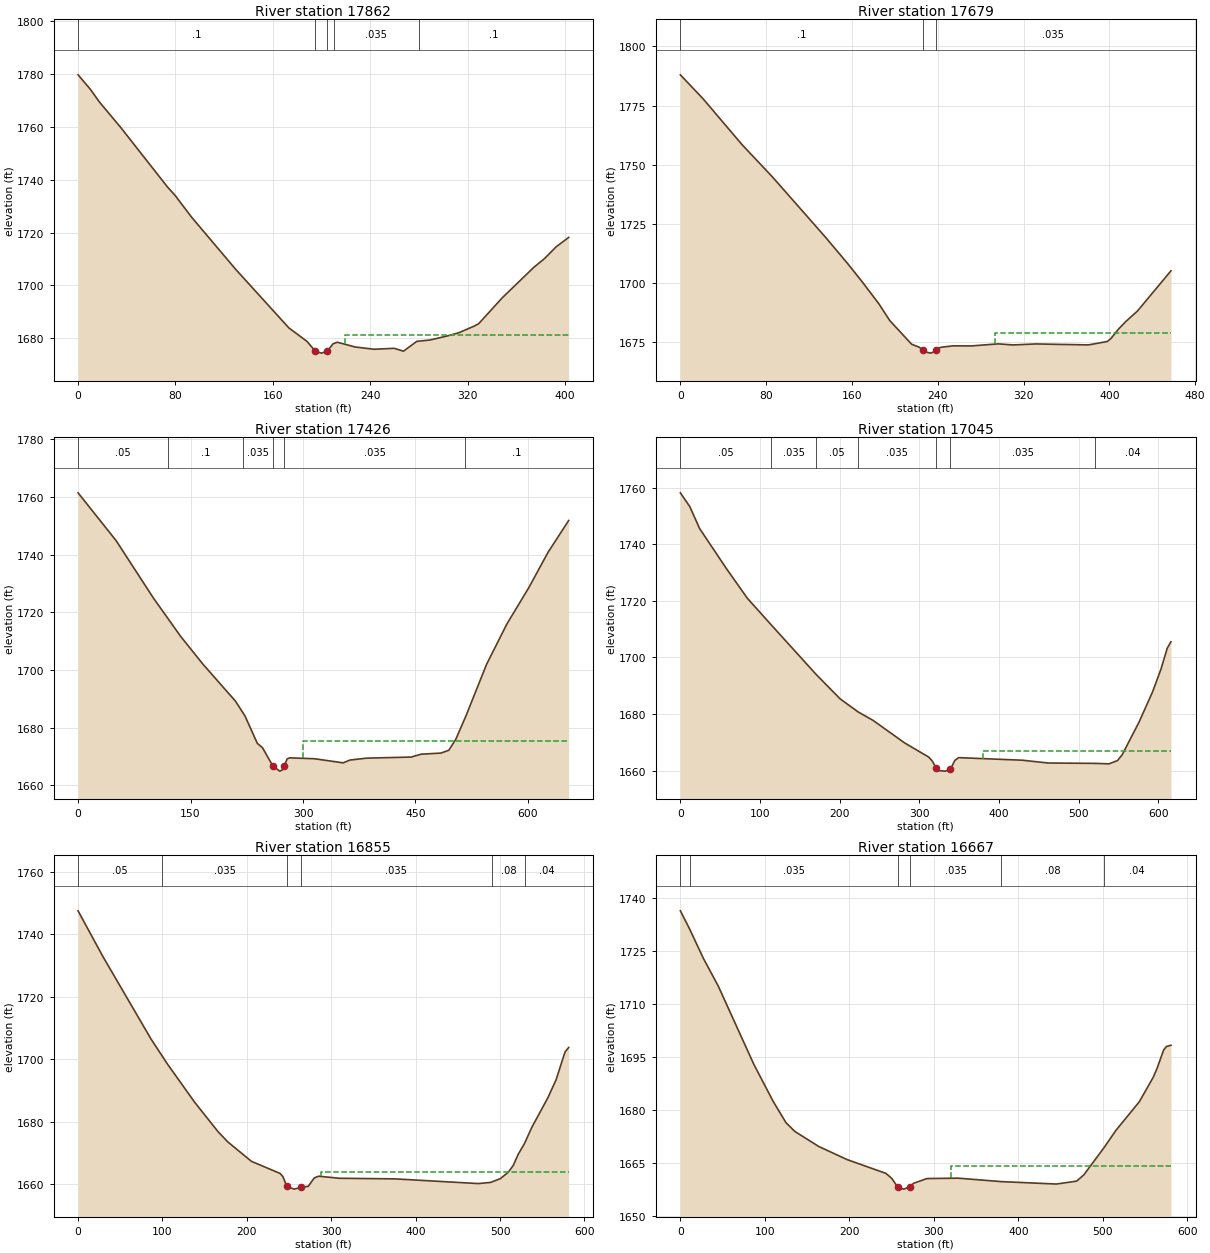
Type RM Length L Ch R = 1 ,17862   ,183.8,183.8,183.8
XS GIS Cut Line= 2
2010444.77871674217971.5682812522010273.46844104 217606.64850874
#Sta/Elev= 30
       0 1779.67    10.1  1774.2    17.4 1769.48    35.5  1759.5    73.4 1737.28
    79.7 1734.07    93.5  1725.7   129.7 1705.99   173.2 1683.94   188.2  1678.8
     195 1675.09     200 1674.39   204.7 1675.11   209.5 1677.93   213.1 1678.51
   227.8  1676.7   243.3 1675.86   259.7 1676.21   267.4 1675.13   278.3 1678.84
   289.2 1679.36   303.7 1680.92   312.8  1682.1   325.4 1684.59   329.1 1685.49
   348.5 1695.31   374.5 1706.86   383.1  1710.1   392.9 1714.64   403.1 1718.17
#Mann= 5 ,-1 , 0
       0      .1       0     195    .045       0   204.7      .1       0
     210    .035       0     280      .1       0
#XS Ineff= 2 , 0
                          219.44         1681.41
Permanent Ineff=
       F       F
Bank Sta=195,204.7
XS Rating Curve= 0 ,0
Exp/Cntr=0.3,0.1

Type RM Length L Ch R = 1 ,17679   ,248.5,252.8,256.8
XS GIS Cut Line= 2
 2010604.7953951217931.1516717262010442.75218692 217503.31063977
#Sta/Elev= 30
       0 1788.02    21.2 1777.89    57.8 1758.39    85.9 1744.88     135 1719.61
     156 1708.31   170.1 1700.28   185.1 1691.33   195.3 1684.22   215.7 1674.22
   222.7 1672.99   226.2 1671.85   229.7 1670.87   233.2 1670.48     236 1670.91
   238.2 1671.76   240.2 1672.58   243.7 1672.99   254.3 1673.56   271.3 1673.52
   296.4 1674.39   310.4 1673.93   331.4 1674.36   380.6 1673.95   398.1 1675.39
   401.6 1676.69   408.6 1680.65   415.6 1683.92   426.2 1688.24   457.5 1705.26
#Mann= 3 ,-1 , 0
       0      .1       0   226.2    .045       0   238.2    .035       0
#XS Ineff= 2 , 0
                          293.25         1679.01
Permanent Ineff=
       F       F
Bank Sta=226.2,238.2
XS Rating Curve= 0 ,0
Exp/Cntr=0.3,0.1

Type RM Length L Ch R = 1 ,17426   ,362.2,381,399.8
XS GIS Cut Line= 3
2010791.53213989217897.8334965722010727.61717476217396.124344115
2010618.94240148   217294.804081
#Sta/Elev= 30
       0 1761.44    50.7 1744.88   100.3 1725.02   136.9 1711.63   166.4 1702.06
   209.8 1689.23   222.6 1684.06   239.1 1674.54   245.8  1673.1   259.71666.757
   268.9 1664.92   272.3 1665.31     2751666.785   278.9 1669.17   282.2 1669.52
   315.2 1669.22   353.6 1667.79   362.4 1668.75   384.7 1669.42   444.2  1669.8
   457.5 1670.79   483.9 1671.18   494.4 1672.15   503.8 1675.99   517.3 1684.07
   544.9 1702.02   571.8  1715.9   601.2 1728.58   626.7 1740.77   654.3 1751.85
#Mann= 6 ,-1 , 0
       0     .05       0     120      .1       0     220    .035       0
   259.7    .045       0     275    .035       0  515.76      .1       0
#XS Ineff= 2 , 0
                          299.35         1675.45
Permanent Ineff=
       F       F
Bank Sta=259.7,275
XS Rating Curve= 0 ,0
Exp/Cntr=0.3,0.1

Type RM Length L Ch R = 1 ,17045   ,193.2,189.9,188.2
XS GIS Cut Line= 3
 2010937.1263002217977.0120432652011067.44273978217742.350597268
2011337.06491968217523.082971157
#Sta/Elev= 30
       0 1758.21    11.8 1753.36    24.2 1745.57      58 1731.35    84.1 1720.94
   114.3 1711.46   170.6 1693.97   200.6 1685.37   223.1 1680.77   241.9 1677.77
   281.5 1669.81   311.9 1664.77   316.5  1663.3   321.2 1660.82   325.2 1659.97
   332.8 1659.83     339 1660.45   344.5 1663.59   349.2  1664.6   429.2 1663.69
   461.7  1662.7   520.9 1662.57   538.1  1662.4   548.8 1663.57   554.7 1665.64
   575.9 1677.21   592.8 1687.86   603.4 1695.93   611.2 1703.27   615.9 1705.56
#Mann= 7 ,-1 , 0
       0     .05       0   114.3    .035       0   170.6     .05       0
   223.1    .035       0   321.2    .045       0     339    .035       0
   520.9     .04       0
#XS Ineff= 2 , 0
                             380            1667
Permanent Ineff=
       F       F
Bank Sta=321.2,339
XS Rating Curve= 0 ,0
Exp/Cntr=0.3,0.1

Type RM Length L Ch R = 1 ,16855   ,188.9,188.2,186
XS GIS Cut Line= 2
2011053.92072399218043.3970159742011447.36846705217615.503738408
#Sta/Elev= 30
       0 1747.55    29.8 1732.73    86.4 1706.51   105.8 1698.52   138.2 1686.22
     166 1676.77   177.6 1673.49   205.5  1667.3   239.3 1663.45   242.7 1662.43
   247.3 1659.28     256 1658.41   263.6 1658.94   272.8 1659.32   279.8 1661.99
   285.1 1662.55   309.4 1661.89     375  1661.7   474.2 1660.19   488.8 1660.56
   500.4 1661.78   509.7 1663.81   515.6 1665.98   521.3 1669.46     529 1673.04
   537.5 1678.13   556.6 1687.65   566.3 1693.38     577 1702.35   581.3 1703.78
#Mann= 6 ,-1 , 0
       0     .05       0     100    .035       0   247.3    .045       0
   263.6    .035       0     490     .08       0     530     .04       0
#XS Ineff= 2 , 0
                             288            1664
Permanent Ineff=
       F       F
Bank Sta=247.3,263.6
XS Rating Curve= 0 ,0
Exp/Cntr=0.3,0.1

Type RM Length L Ch R = 1 ,16667   ,224.1,224.9,222.9
XS GIS Cut Line= 2
2011210.69187486218181.7925777662011561.83211072217719.238176615
#Sta/Elev= 30
       0 1736.28    11.1 1731.07    27.3 1722.81    44.8 1715.03      87 1692.87
   109.8 1682.43     125 1676.39   135.4 1673.93   163.7 1669.67   197.2 1665.97
   243.3 1662.05   250.3 1660.62   257.4 1658.12   264.4  1657.6   271.3  1658.2
   276.1 1659.26   291.9 1660.59     329  1660.7     380 1659.72   445.1 1659.04
     469 1659.86   477.5 1661.62   500.9 1669.14   515.7 1674.26   543.2 1682.29
   559.7 1689.22   564.1 1691.65     572 1696.93   575.4 1697.94   580.7 1698.28
#Mann= 6 ,-1 , 0
       0      .1       0    11.1    .035       0   257.4    .045       0
   271.3    .035       0     380     .08       0   500.9     .04       0
#XS Ineff= 2 , 0
                             320            1664
Permanent Ineff=
       F       F
Bank Sta=257.4,271.3
XS Rating Curve= 0 ,0
Exp/Cntr=0.3,0.1

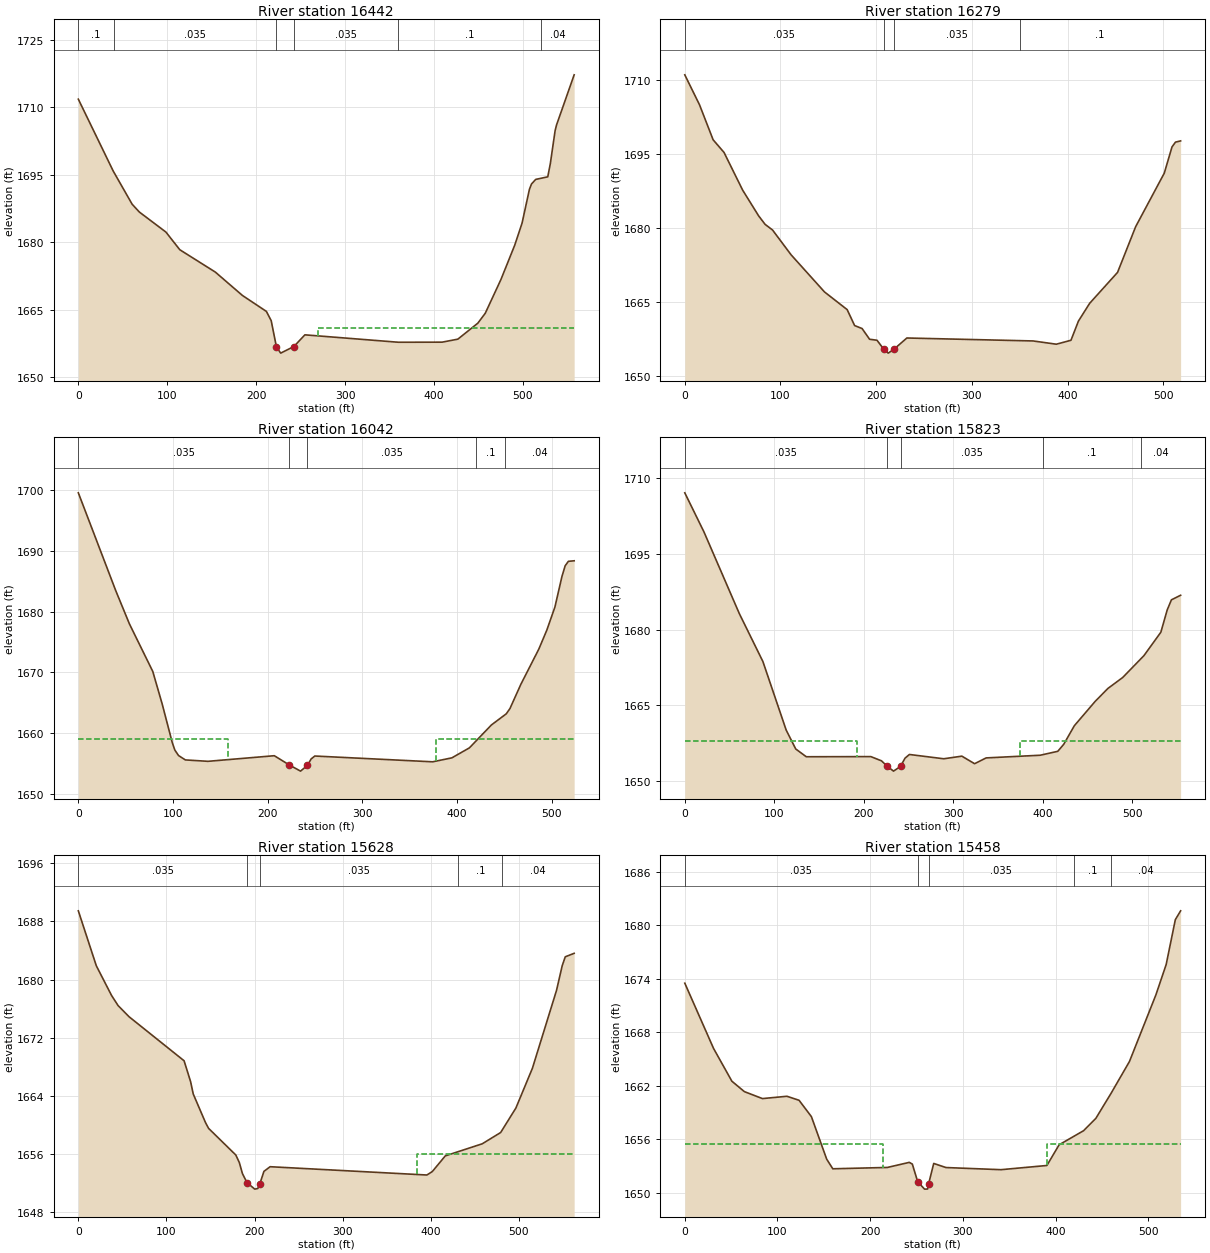
Type RM Length L Ch R = 1 ,16442   ,163.4,163.3,163
XS GIS Cut Line= 2
2011390.31299785218305.5052661282011730.15808756 217863.43194109
#Sta/Elev= 30
       0 1711.82    39.2 1695.84    60.5 1688.45    68.6 1686.71    98.5 1682.25
   114.1 1678.32   154.1 1673.34   184.5 1668.15   211.5 1664.59   216.9 1662.53
   222.8 1656.68   227.6 1655.31   242.4 1656.78   254.8 1659.38     360 1657.73
   409.1 1657.75   426.8 1658.42   449.3 1661.98   457.6 1664.17   475.3 1671.71
   490.7  1679.3     499 1684.23   507.3 1691.77   509.7 1692.97   514.4 1693.97
   527.9 1694.54   530.8 1697.47   536.2 1704.84   537.8 1706.09   557.6 1717.24
#Mann= 6 ,-1 , 0
       0      .1       0      40    .035       0   222.8    .045       0
   242.4    .035       0     360      .1       0     520     .04       0
#XS Ineff= 2 , 0
                             270            1661
Permanent Ineff=
       F       F
Bank Sta=222.8,242.4
XS Rating Curve= 0 ,0
Exp/Cntr=0.3,0.1

Type RM Length L Ch R = 1 ,16279   ,227.2,236.9,243.5
XS GIS Cut Line= 2
  2011519.323712218423.4063638322011799.35871712217987.409093309
#Sta/Elev= 30
       0 1711.04    15.4 1704.95    29.6 1697.86      41 1695.29    60.5 1687.63
    77.1 1682.44    83.9  1680.7    91.7 1679.55   111.2 1674.49     146 1666.98
   169.7 1663.39   177.5 1660.15   185.3 1659.55   193.1 1657.38   200.9 1657.17
   207.7 1655.42   212.6 1654.56   218.4 1655.32   232.1 1657.63   364.1 1657.03
   388.3 1656.37   403.6 1657.17   411.4 1661.06   423.1 1664.66   452.3 1670.95
   471.2 1680.22   501.1 1691.08   509.2 1696.41   512.8 1697.38   518.2 1697.63
#Mann= 4 ,-1 , 0
       0    .035       0   207.7    .045       0   218.4    .035       0
     350      .1       0
Bank Sta=207.7,218.4
XS Rating Curve= 0 ,0
Exp/Cntr=0.3,0.1

Type RM Length L Ch R = 1 ,16042   ,219,218.7,205.7
XS GIS Cut Line= 2
 2011623.4661251218498.7574798042012065.30696362218217.963721364
#Sta/Elev= 30
       0  1699.5    39.6  1683.4      54 1677.96    78.6 1670.17    88.6 1664.79
    99.1 1658.53   101.9 1657.26   105.8 1656.36     113 1655.64   136.9 1655.41
   206.9 1656.33   222.4 1654.85   234.6  1653.8   241.9 1654.74   245.8  1655.8
   249.7 1656.28   374.1 1655.33   394.4 1655.98   412.9 1657.62   436.2 1661.39
   451.8 1663.21   455.7 1664.07   467.3 1668.08   486.2 1673.84   494.6 1676.94
   503.2 1680.75   510.6 1685.76     514 1687.52   517.4 1688.25   523.5 1688.34
#Mann= 5 ,-1 , 0
       0    .035       0   222.4    .045       0   241.9    .035       0
     420      .1       0     450     .04       0
#XS Ineff= 2 , 0
             158    1659     378            1659
Permanent Ineff=
       F       F
Bank Sta=222.4,241.9
XS Rating Curve= 0 ,0
Exp/Cntr=0.3,0.1

Type RM Length L Ch R = 1 ,15823   ,199.9,195.4,191.5
XS GIS Cut Line= 2
2011780.31694886 218695.543093022012087.45283189218234.245888162
#Sta/Elev= 30
       0 1707.14    21.5 1699.36    60.9 1683.21    87.3 1673.69   113.3 1660.11
     124 1656.35   135.8 1654.81   207.9 1654.84   219.8 1654.01   226.5 1652.89
   233.3 1651.96   241.1  1652.9   246.2 1654.54   251.1 1655.26   289.5 1654.41
   309.7 1654.93   323.9 1653.43   336.8 1654.58   397.2 1655.11   416.9 1655.89
   423.6 1657.29   435.4 1660.96   458.7 1665.79   472.9 1668.35   489.5 1670.53
   513.2 1674.86   532.1  1679.5   539.2 1683.92   543.9 1685.92   554.2 1686.83
#Mann= 5 ,-1 , 0
       0    .035       0   226.5    .045       0   241.1    .035       0
     400      .1       0     510     .04       0
#XS Ineff= 2 , 0
             192    1658     375            1658
Permanent Ineff=
       F       F
Bank Sta=226.5,241.1
XS Rating Curve= 0 ,0
Exp/Cntr=0.3,0.1

Type RM Length L Ch R = 1 ,15628   ,173.1,169.8,165
XS GIS Cut Line= 3
2011891.14958956 218764.912459292011992.28178237218718.673280758
2012145.54015702218294.076685605
#Sta/Elev= 30
       0 1689.44    20.4 1681.89    37.7 1677.81    45.1 1676.42    57.5 1674.89
     120 1668.83   127.4 1665.96   130.4 1664.26   144.4 1660.31   147.8 1659.54
   178.7 1655.88   182.7 1654.84   186.2 1653.33   191.4 1652.08   200.2 1651.19
   203.7 1651.28     206 1651.94   210.6 1653.63   217.6 1654.27   395.5 1653.13
   401.6  1653.6   416.4 1655.76   458.3 1657.42   479.2 1658.97   496.5 1662.34
   515.2 1667.79   542.6 1678.51     549 1681.88   552.5 1683.12   562.6  1683.6
#Mann= 5 ,-1 , 0
       0    .035       0   191.4    .045       0     206    .035       0
   431.2      .1       0   481.2     .04       0
#XS Ineff= 2 , 0
                             384            1656
Permanent Ineff=
       F       F
Bank Sta=191.4,206
XS Rating Curve= 0 ,0
Exp/Cntr=0.3,0.1

Type RM Length L Ch R = 1 ,15458   ,198.3,198.8,192.2
XS GIS Cut Line= 2
2012149.10841852218882.3076631242012206.59271198 218350.44098903
#Sta/Elev= 30
       0  1673.5      31 1666.19    50.8 1662.51    64.3 1661.34    83.8 1660.56
   110.2 1660.82   123.3 1660.37   136.6 1658.54   153.1 1653.77   159.7 1652.69
   218.6 1652.84   242.2 1653.41   245.5 1653.22   251.3 1651.24   258.7 1650.41
     262 1650.42     2631650.969   268.6 1653.29   281.8 1652.83   341.2 1652.59
   390.7 1653.06   403.9 1655.38   430.3 1656.96   443.5 1658.34     460 1661.16
   479.8 1664.72   508.3 1672.18   519.4 1675.59   529.3 1680.62     535 1681.61
#Mann= 5 ,-1 , 0
       0    .035       0   251.3    .045       0     263    .035       0
     420      .1       0     460     .04       0
#XS Ineff= 2 , 0
           213.5  1655.5     391          1655.5
Permanent Ineff=
       F       F
Bank Sta=251.3,263
XS Rating Curve= 0 ,0
Exp/Cntr=0.3,0.1

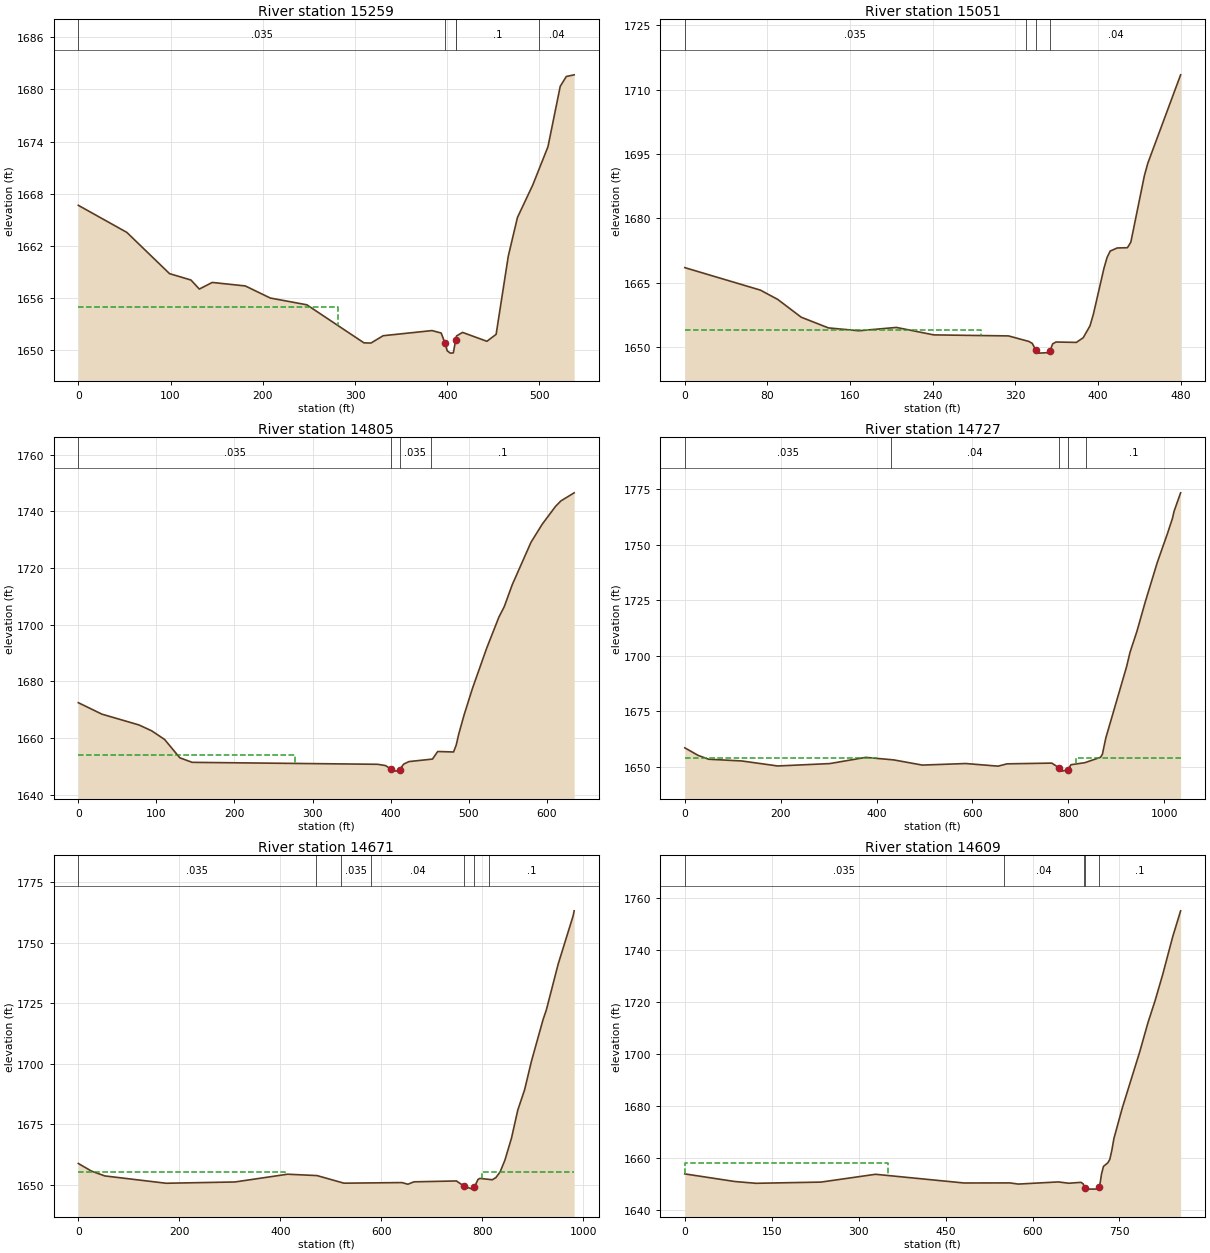
Type RM Length L Ch R = 1 ,15259   ,205.6,208.2,211.1
XS GIS Cut Line= 2
2012398.40103257218969.2703424182012328.44515736218436.226135859
#Sta/Elev= 30
       0 1666.67    52.6 1663.56    98.9 1658.82   122.1 1658.09   131.2 1657.05
   145.2 1657.81     181 1657.41   208.1 1656.02   247.8 1655.24   309.7 1650.87
   317.3 1650.85   330.5 1651.69   383.5 1652.28   393.4    1652   397.4 1650.89
     400 1649.95   403.3 1649.69   406.6 1649.72   409.1 1651.18     410 1651.66
   416.6 1652.07     443 1651.05     453 1651.85   466.2 1660.84   476.1 1665.27
   492.7    1669   509.2  1673.4   522.5 1680.34   529.1 1681.47   537.6 1681.66
#Mann= 5 ,-1 , 0
       0    .035       0   397.4    .045       0   409.1    .035       0
     410      .1       0     500     .04       0
#XS Ineff= 2 , 0
             282    1655
Permanent Ineff=
       F       F
Bank Sta=397.4,409.1
XS Rating Curve= 0 ,0
Exp/Cntr=0.3,0.1

Type RM Length L Ch R = 1 ,15051   ,241.6,245.4,246.9
XS GIS Cut Line= 2
 2012493.3374263 218993.433732822012528.34175474218514.742527355
#Sta/Elev= 30
       0 1668.51    73.2 1663.27      90  1661.1   112.7 1656.96     139 1654.47
   168.6  1653.8   204.8 1654.58     241 1652.84   313.4  1652.6   333.1 1651.31
   336.4 1650.86   339.7 1649.33     343 1648.59   352.8 1648.72   353.6 1649.15
   356.1 1650.75   359.4 1651.18   379.1 1651.09   385.7 1652.18   392.3 1654.97
   395.6 1657.72   405.7 1668.28   408.8 1670.88   411.8 1672.37   418.6 1673.09
   428.5 1673.15   431.8 1674.45   444.9 1689.91   448.2 1692.81     480 1713.43
#Mann= 4 ,-1 , 0
       0    .035       0     330     .04       0   339.7    .045       0
   353.6     .04       0
#XS Ineff= 2 , 0
           286.5    1654
Permanent Ineff=
       F       F
Bank Sta=339.7,353.6
XS Rating Curve= 0 ,0
Exp/Cntr=0.3,0.1

Type RM Length L Ch R = 1 ,14805   ,90,78.3,67.8
XS GIS Cut Line= 4
2012512.33813078219050.2075339042012724.50839866  218744.5676795
2012742.95997142218648.3728866732012696.17083347218490.006419752
#Sta/Elev= 30
       0 1672.46    30.2 1668.42    77.5 1664.62      94 1662.53   110.5 1659.48
     130 1653.02   145.8 1651.41   383.5 1650.72   393.5 1650.27   400.1 1649.08
   406.8 1648.31   411.4 1648.83   416.8 1650.79   423.5 1651.68   453.6 1652.56
   460.3 1655.23   480.6 1655.07     484 1657.48   487.4 1661.53   494.2 1668.21
   504.7  1677.4     523 1691.66   538.7 1702.66   545.6 1706.37   555.8  1714.1
   579.8 1729.06   594.3 1735.49   611.2 1741.72   618.1 1743.67   635.1 1746.52
#Mann= 4 ,-1 , 0
       0    .035       0   400.1    .045       0   411.4    .035       0
  452.06      .1       0
#XS Ineff= 2 , 0
             277    1654
Permanent Ineff=
       F       F
Bank Sta=400.1,411.4
XS Rating Curve= 0 ,0
Exp/Cntr=0.5,0.3

Type RM Length L Ch R = 1 ,14727   ,54.2,55.8,56.2
XS GIS Cut Line= 4
 2013453.7506674219136.7546449972012846.24741375218795.353991515
2012753.86838492218601.9558677252012799.92689779218487.862290824
#Sta/Elev= 30
       0 1658.57    27.9 1655.17    49.6 1653.45   119.1 1652.66   193.8 1650.41
   302.6 1651.49   377.3 1654.28   435.7 1653.15   495.4 1650.81   585.8 1651.51
   653.5 1650.33   672.3 1651.37   765.5  1651.7     781 1649.52   787.3 1648.09
   799.11648.796   805.5 1650.97   834.6  1651.9   867.3 1654.34     871 1655.69
   878.2 1663.05   921.6 1695.19   928.6 1701.55     943 1710.99   960.5  1724.3
   985.3 1741.88  1006.5 1754.89  1017.1  1761.8  1020.6  1765.1  1034.2 1773.36
#Mann= 5 ,-1 , 0
       0    .035       0     430     .04       0     781    .045       0
   799.1     .04       0  836.86      .1       0
#XS Ineff= 2 , 0
             400    1654     815            1654
Permanent Ineff=
       F       F
Bank Sta=781,799.1
XS Rating Curve= 0 ,0
Exp/Cntr(USF)=0,0
Exp/Cntr=0.5,0.3

Type RM Length L Ch R = 1 ,14671   ,62.5,62.1,64
XS GIS Cut Line= 4
2013493.95679497219106.4851769042012897.57974532218792.909366058
 2012815.3635485218594.3659971392012824.98459281218501.654115617
#Sta/Elev= 30
       0 1658.72    26.2 1655.55    52.5 1653.57   173.9 1650.54     310 1651.07
   414.5 1654.28   472.8 1653.71     526 1650.57   640.9 1650.82   652.6 1650.14
   664.7 1651.13   748.8 1651.49     7641649.326   780.8 1648.11   784.4 1648.98
   791.5  1652.1   795.1 1652.54   819.9 1651.99     827 1652.91   835.2 1655.22
   844.7 1660.06   857.8 1669.22   870.3 1680.83   883.8 1689.24   897.3 1701.01
   920.2 1718.16     927 1722.38   950.1 1741.11   979.8 1761.12   981.9 1763.24
#Mann= 7 ,-1 , 0
       0    .035       0     470     .04       0     520    .035       0
     580     .04       0     764    .045       0   784.4     .04       0
  813.79      .1       0
#XS Ineff= 2 ,-1
       0     409    1655     800  981.89    1655
Permanent Ineff=
       F       F
Bank Sta=764,784.4
XS Rating Curve= 0 ,0
Exp/Cntr(USF)=0,0
Exp/Cntr=0.5,0.3

Type RM Length L Ch R = 1 ,14609   ,372.6,375.3,370.3
XS GIS Cut Line= 4
2013463.95724434219045.3240980122012947.59414596 218762.00173798
2012879.94162788218597.2487703272012879.46736375218508.749750823
#Sta/Elev= 30
       0 1653.92    86.6 1650.99   122.8 1650.31   234.9 1650.77   329.1 1653.77
   481.8 1650.43   561.2 1650.46   575.4 1650.01   644.7 1650.84   662.5 1650.33
   683.7 1650.68   687.3 1650.12   690.8 1648.43   694.4 1648.07   711.4  1648.1
   714.9 1648.74   715.7 1648.99   719.2 1653.99   722.5 1656.81     730 1658.19
   733.4  1659.5   736.9 1662.96   740.5 1667.53   754.7 1679.07   785.1 1700.86
   799.2 1711.98   811.4 1720.36   824.5 1730.36   842.1 1745.14   855.6 1754.96
#Mann= 5 ,-1 , 0
       0    .035       0     550     .04       0  688.98      .1       0
   690.8    .045       0   714.9      .1       0
#XS Ineff= 2 , 0
             350    1658
Permanent Ineff=
       F       F
Bank Sta=690.8,714.9
XS Rating Curve= 0 ,0
Exp/Cntr(USF)=0,0
Exp/Cntr=0.3,0.1

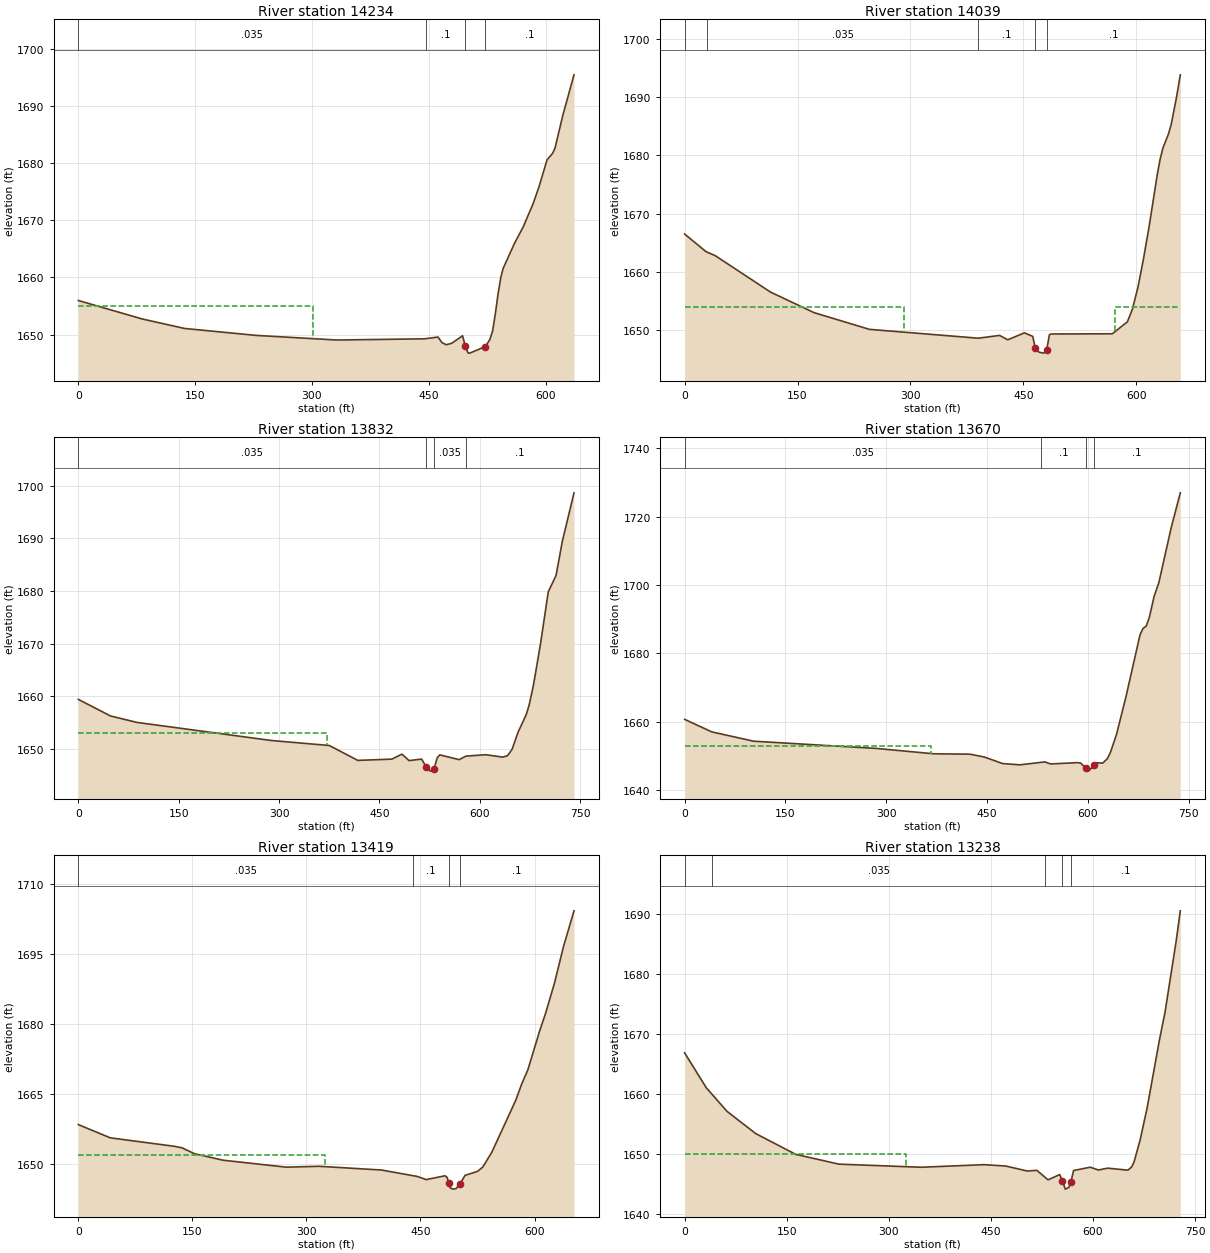
Type RM Length L Ch R = 1 ,14234   ,197,194.6,195
XS GIS Cut Line= 3
2013520.94673351219022.6588901322013347.14490666218862.880597395
2013206.39970269218487.885018041
#Sta/Elev= 30
       0 1655.98      82 1652.75   136.5 1651.09   228.2 1649.88   331.9 1649.07
   444.5 1649.28   461.9 1649.59     467 1648.62   472.5 1648.24   479.5  1648.5
   493.5 1649.82   497.11647.962   500.5  1646.8   502.7 1646.78   522.81647.933
   528.6 1649.17   532.1 1650.68   535.6 1653.68   539.1 1657.17   542.6    1660
   545.6 1661.58   560.1 1665.95   571.4 1668.85   584.2 1672.94   591.8 1675.92
     602 1680.57   609.2 1681.71   612.2 1682.61   622.4 1688.42   636.6 1695.42
#Mann= 4 ,-1 , 0
       0    .035       0  446.09      .1       0   497.1    .045       0
   522.8      .1       0
#XS Ineff= 2 , 0
           301.5    1655
Permanent Ineff=
       F       F
Bank Sta=497.1,522.8
XS Rating Curve= 0 ,0
Exp/Cntr=0.3,0.1

Type RM Length L Ch R = 1 ,14039   ,213.3,207.1,200
XS GIS Cut Line= 2
 2013651.9497365218988.3378115832013354.20673686218401.105794057
#Sta/Elev= 30
       0 1666.52    28.3 1663.51    40.9 1662.79   114.1 1656.56   171.8 1653.04
   245.4 1650.17     390 1648.65   418.3 1649.13   429.3 1648.38   451.4 1649.57
   462.4 1648.96   465.6 1647.05   470.5 1646.26   477.1 1646.09   480.8 1646.58
   484.5 1649.22   486.5 1649.37   568.1 1649.41   588.1 1651.46   594.8 1653.65
   602.2 1657.42   609.6 1662.34     617 1667.84   627.9 1676.78   631.6 1679.35
   635.3 1681.27   642.6 1683.65   646.3 1685.32   653.4 1690.01   658.4 1693.83
#Mann= 5 ,-1 , 0
       0     .04       0      30    .035       0     390      .1       0
   465.6    .045       0   480.8      .1       0
#XS Ineff= 2 , 0
             292    1654     572            1654
Permanent Ineff=
       F       F
Bank Sta=465.6,480.8
XS Rating Curve= 0 ,0
Exp/Cntr=0.3,0.1

Type RM Length L Ch R = 1 ,13832   ,160.9,162.3,163.8
XS GIS Cut Line= 2
2014024.27349124218802.3173214132013441.54664283218344.914246686
#Sta/Elev= 30
       0 1659.39    48.1 1656.24    87.7 1655.01   288.7 1651.57   375.1 1650.62
   417.7 1647.79   468.6 1648.03   483.6 1648.98   494.3 1647.75     513 1648.04
     520 1646.56   526.1 1645.75   531.7 1646.23   536.4  1648.3   540.3 1648.84
   569.1 1647.93   579.2  1648.6   608.8 1648.87   634.5 1648.41   641.5 1648.69
   648.3  1649.9   657.1 1653.12   669.6 1656.54   673.8 1658.34   680.2  1662.1
   690.8 1669.99   702.3 1679.82     714 1682.96   723.3 1689.41   740.8 1698.66
#Mann= 4 ,-1 , 0
       0    .035       0     520    .045       0   531.7    .035       0
     580      .1       0
#XS Ineff= 2 , 0
             371    1653
Permanent Ineff=
       F       F
Bank Sta=520,531.7
XS Rating Curve= 0 ,0
Exp/Cntr=0.3,0.1

Type RM Length L Ch R = 1 ,13670   ,247.2,250.4,253.9
XS GIS Cut Line= 2
2014075.07311053218732.6153745972013532.63457132218233.063770426
#Sta/Elev= 30
       0 1660.68    40.3 1657.01   102.7 1654.28   285.6 1652.16   370.3  1650.6
   424.4 1650.48   446.1 1649.64   472.9 1647.74   498.7 1647.36   535.9 1648.22
   544.3 1647.62   584.8 1648.01   589.3 1647.87   596.51646.426   600.9 1645.52
   608.81647.205   612.5 1647.97   621.8 1647.85     629 1649.19   633.5 1651.03
   642.4 1656.21   656.6 1667.32   677.5 1685.45   681.7  1687.2   686.8 1688.03
   691.4  1690.6   698.4 1696.66   705.4 1700.64   723.9 1716.84   737.4 1726.99
#Mann= 4 ,-1 , 0
       0    .035       0     530      .1       0   596.5    .045       0
   608.8      .1       0
#XS Ineff= 2 , 0
             367    1653
Permanent Ineff=
       F       F
Bank Sta=596.5,608.8
XS Rating Curve= 0 ,0
Exp/Cntr=0.3,0.1

Type RM Length L Ch R = 1 ,13419   ,181.7,181.3,180.4
XS GIS Cut Line= 2
2014110.39631445218647.1140156442013753.30233364 218101.69264637
#Sta/Elev= 30
       0 1658.46      42 1655.62   126.8  1653.8   136.2 1653.49   152.8 1652.22
   190.4 1650.83   273.7 1649.34   316.5 1649.53   398.8 1648.73   445.9 1647.35
   457.6 1646.68   482.3  1647.5   485.1 1647.14     487 1646.04     489 1644.93
   492.9 1644.64   496.8 1644.76   501.9 1645.71   508.6 1647.59   524.9 1648.43
     532 1649.38   543.9 1652.57   575.3 1663.66   583.1 1667.15   591.3 1670.22
   606.6 1678.45   614.5 1682.27   626.3 1688.79     638 1696.53   651.9 1704.22
#Mann= 4 ,-1 , 0
       0    .035       0     440      .1       0     487    .045       0
   501.9      .1       0
#XS Ineff= 2 , 0
             325    1652
Permanent Ineff=
       F       F
Bank Sta=487,501.9
XS Rating Curve= 0 ,0
Exp/Cntr=0.3,0.1

Type RM Length L Ch R = 1 ,13238   ,288.5,289.9,290.3
XS GIS Cut Line= 2
2014331.31623761218603.4693156932013900.22599809218016.428875022
#Sta/Elev= 30
       0 1666.88    31.7 1661.08    62.3 1657.12   104.5 1653.41   163.2 1649.95
   226.5 1648.32   347.6  1647.8   440.1 1648.23   471.9    1648   503.5 1647.17
   517.6 1647.28     534  1645.7   551.1 1646.58   555.1 1645.51   559.3 1644.15
   564.5 1644.43   567.4 1645.28   571.5 1647.25   595.9 1647.81   608.1 1647.34
   621.5 1647.65   651.3 1647.31     657 1647.88   660.3 1648.67   669.2 1652.32
   679.5 1657.67   697.7 1669.07   705.8 1673.63   722.1 1685.45   728.3 1690.57
#Mann= 5 ,-1 , 0
       0     .04       0      40    .035       0     530      .1       0
   555.1    .045       0   567.4      .1       0
#XS Ineff= 2 , 0
             325    1650
Permanent Ineff=
       F       F
Bank Sta=555.1,567.4
XS Rating Curve= 0 ,0
Exp/Cntr=0.3,0.1

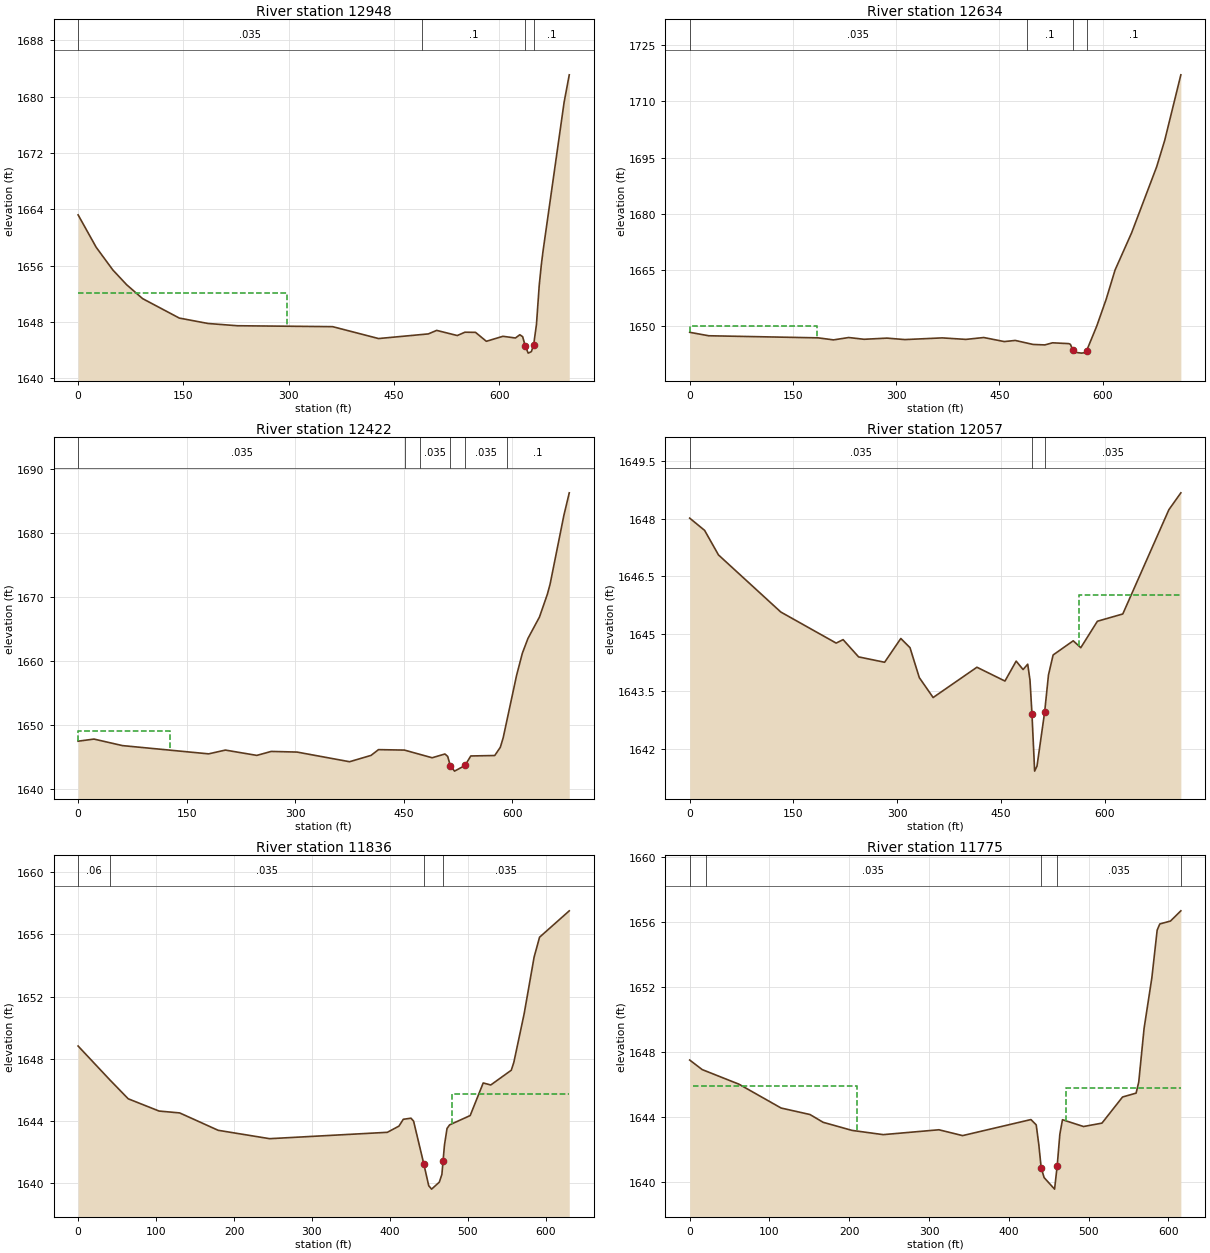
Type RM Length L Ch R = 1 ,12948   ,302.6,314,311.2
XS GIS Cut Line= 2
2014531.98190606218469.4738164992014143.96107274217887.442566514
#Sta/Elev= 30
       0 1663.22    25.8 1658.61    49.5 1655.39    69.2 1653.29    91.9 1651.32
   144.1 1648.56   185.1 1647.79   226.8 1647.47   362.5 1647.34   427.9 1645.65
   498.8 1646.31   510.7 1646.81     540 1646.08   550.9 1646.55     566 1646.53
   581.4 1645.26     605 1645.97   622.8 1645.73   629.1 1646.19   633.1 1645.92
     637 1644.55     641 1643.58   645.5 1643.79   648.8 1644.77   652.8 1647.67
   656.7 1653.17   659.7 1656.12   662.1 1658.04   692.2 1679.24   699.5 1683.11
#Mann= 4 ,-1 , 0
       0    .035       0     490      .1       0     637    .045       0
   648.8      .1       0
#XS Ineff= 2 , 0
          297.82 1652.17
Permanent Ineff=
       F       F
Bank Sta=637,648.8
XS Rating Curve= 0 ,0
Exp/Cntr(USF)=0,0
Exp/Cntr=0.3,0.1

Type RM Length L Ch R = 1 ,12634   ,211.6,212.5,209.5
XS GIS Cut Line= 2
2014687.98052878218298.5368122942014357.20562352217666.001397918
#Sta/Elev= 30
       0 1648.45    27.6 1647.53   186.8 1646.97     209 1646.43   231.2 1647.06
   253.4 1646.59   286.8  1646.9   312.7 1646.51     367 1646.96   401.5 1646.56
   427.4 1647.06   457.1 1645.98   473.2 1646.28   499.1 1645.21   516.1 1645.09
   527.4 1645.65   551.1 1645.43   553.3 1645.23     557 1643.64   560.7 1643.11
   569.6  1642.9   574.4 1643.02   576.9 1643.56   591.5 1650.08   605.2 1657.22
   618.2 1665.06   642.2 1674.95   678.6 1692.55   690.3 1699.59   713.8 1717.08
#Mann= 4 ,-1 , 0
       0    .035       0     490      .1       0     557    .045       0
   576.9      .1       0
#XS Ineff= 2 , 0
           185.5    1650
Permanent Ineff=
       F       F
Bank Sta=557,576.9
XS Rating Curve= 0 ,0
Exp/Cntr=0.3,0.1

Type RM Length L Ch R = 1 ,12422   ,347.2,365,376.5
XS GIS Cut Line= 3
2014721.00033422218243.4995923322014676.70434507217833.581228203
 2014539.8901059217605.022518884
#Sta/Elev= 30
       0 1647.48      22 1647.81    61.3 1646.79   180.4  1645.5   203.5 1646.09
     247 1645.26   266.8 1645.88   302.5 1645.78   375.1 1644.27   404.8 1645.26
   415.1 1646.16   450.9 1646.09   489.2 1644.89   506.9 1645.48   510.7  1645.1
   514.5 1643.59   520.2  1642.8   534.6 1643.68   542.6 1645.17   575.7 1645.24
   583.4 1646.52   587.4 1648.02   605.9 1657.77   613.9 1661.24   621.6 1663.54
   637.5 1666.89   648.4 1670.44   652.2 1672.03   671.3 1682.81   678.7 1686.31
#Mann= 6 ,-1 , 0
       0    .035       0   452.3      .1       0   472.3    .035       0
   514.5    .045       0   534.6    .035       0   592.3      .1       0
#XS Ineff= 2 , 0
             127    1649
Permanent Ineff=
       F       F
Bank Sta=514.5,534.6
XS Rating Curve= 0 ,0
Exp/Cntr=0.3,0.1

Type RM Length L Ch R = 1 ,12057   ,225.2,220.3,213.5
XS GIS Cut Line= 2
2014812.86092166218255.9577373032014940.42817549217557.669244305
#Sta/Elev= 30
       0 1648.01    21.6 1647.69    41.6 1647.05   131.7 1645.56   211.7 1644.75
   221.7 1644.84   244.1 1644.39   281.7 1644.25   305.1 1644.87   318.4 1644.63
   331.8 1643.85   351.8 1643.33   415.1 1644.12   455.6 1643.76   471.8 1644.28
   481.8 1644.06   488.5  1644.2   491.8 1643.78   494.6 1642.91   498.5 1641.41
   501.9 1641.54   512.9 1642.94   518.5 1643.92   525.2 1644.44   554.3 1644.81
   565.2 1644.63   589.2 1645.32   625.9 1645.51   692.5 1648.23   709.8 1648.67
#Mann= 3 ,-1 , 0
       0    .035       0   494.6    .045       0   512.9    .035       0
#XS Ineff= 2 , 0
                             562            1646
Permanent Ineff=
       F       F
Bank Sta=494.6,512.9
XS Rating Curve= 0 ,0
Exp/Cntr(USF)=0,0
Exp/Cntr=0.5,0.3

Type RM Length L Ch R = 1 ,11836   ,61,61.1,61.8
XS GIS Cut Line= 2
2015164.86095075218203.5340307752015100.14888401217576.725062602
#Sta/Elev= 30
       0 1648.81    40.9 1646.62    64.3 1645.41   103.9 1644.62   130.3  1644.5
   179.7 1643.38   245.7 1642.84   396.7 1643.25   411.6 1643.65   417.2 1644.09
   427.1 1644.16   430.4 1643.97   443.6 1641.19   449.8 1639.81   453.5 1639.59
   463.4 1640.04   466.7 1640.54   468.2 1641.41     470 1642.43   473.3  1643.5
   476.6 1643.73     503 1644.33   519.7 1646.43   529.4  1646.3   555.7 1647.25
     559 1647.76   572.2 1650.88     585 1654.54     592 1655.82   630.1 1657.52
#Mann= 4 ,-1 , 0
       0     .06       0    40.9    .035       0   443.6    .045       0
   468.2    .035       0
#XS Ineff= 2 ,-1
     140   431.6  1643.5   480.2  630.14  1645.7
Permanent Ineff=
       F       F
Bank Sta=443.6,468.2
XS Rating Curve= 0 ,0
Exp/Cntr(USF)=0,0
Exp/Cntr=0.5,0.3

Type RM Length L Ch R = 1 ,11775   ,134.7,133.4,131.9
XS GIS Cut Line= 2
 2015223.5298673 218197.826611142015163.09836528217585.118326771
#Sta/Elev= 30
       0  1647.5    15.7 1646.91    61.8 1646.01   114.6 1644.54   150.8 1644.14
   167.3 1643.66   203.6 1643.16   242.6  1642.9   312.4  1643.2   342.1 1642.84
   427.8 1643.83   434.4  1643.5   437.6  1642.3   440.6 1640.86   444.3 1640.25
   457.4 1639.54   460.7 1640.98     464 1642.92   467.3 1643.82   493.7  1643.4
   516.8 1643.61   542.6 1645.22   559.6 1645.46   562.9 1646.14   569.6 1649.45
   579.4 1652.59     586 1655.51   589.3 1655.89   602.7 1656.07   615.7  1656.7
#Mann= 5 ,-1 , 0
       0     .06       0      20    .035       0   440.6    .045       0
   460.7    .035       0  615.68      .1       0
#XS Ineff= 2 ,-1
    3.81  209.47 1645.87   471.7 615.681  1645.8
Permanent Ineff=
       F       F
Bank Sta=440.6,460.7
XS Rating Curve= 0 ,0
Exp/Cntr(USF)=0,0
Exp/Cntr=0.5,0.3