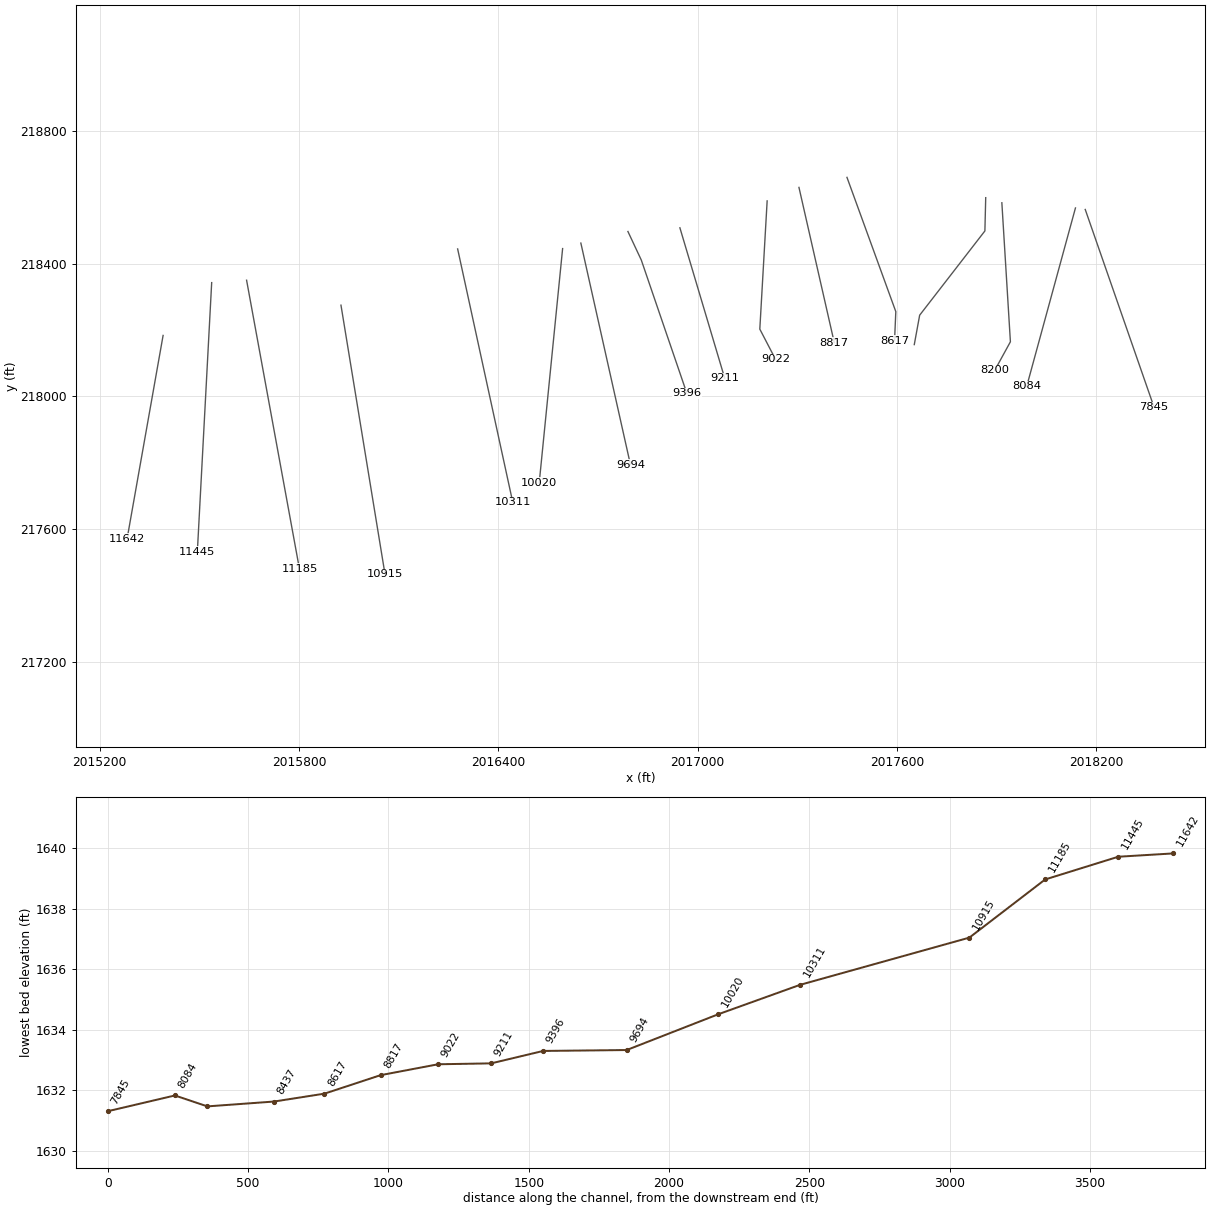
HEC-RAS study WOLFCK_A.prj: WOLFCK_A

--- WOLFCK_A.g01 (geometry) --- (continued)

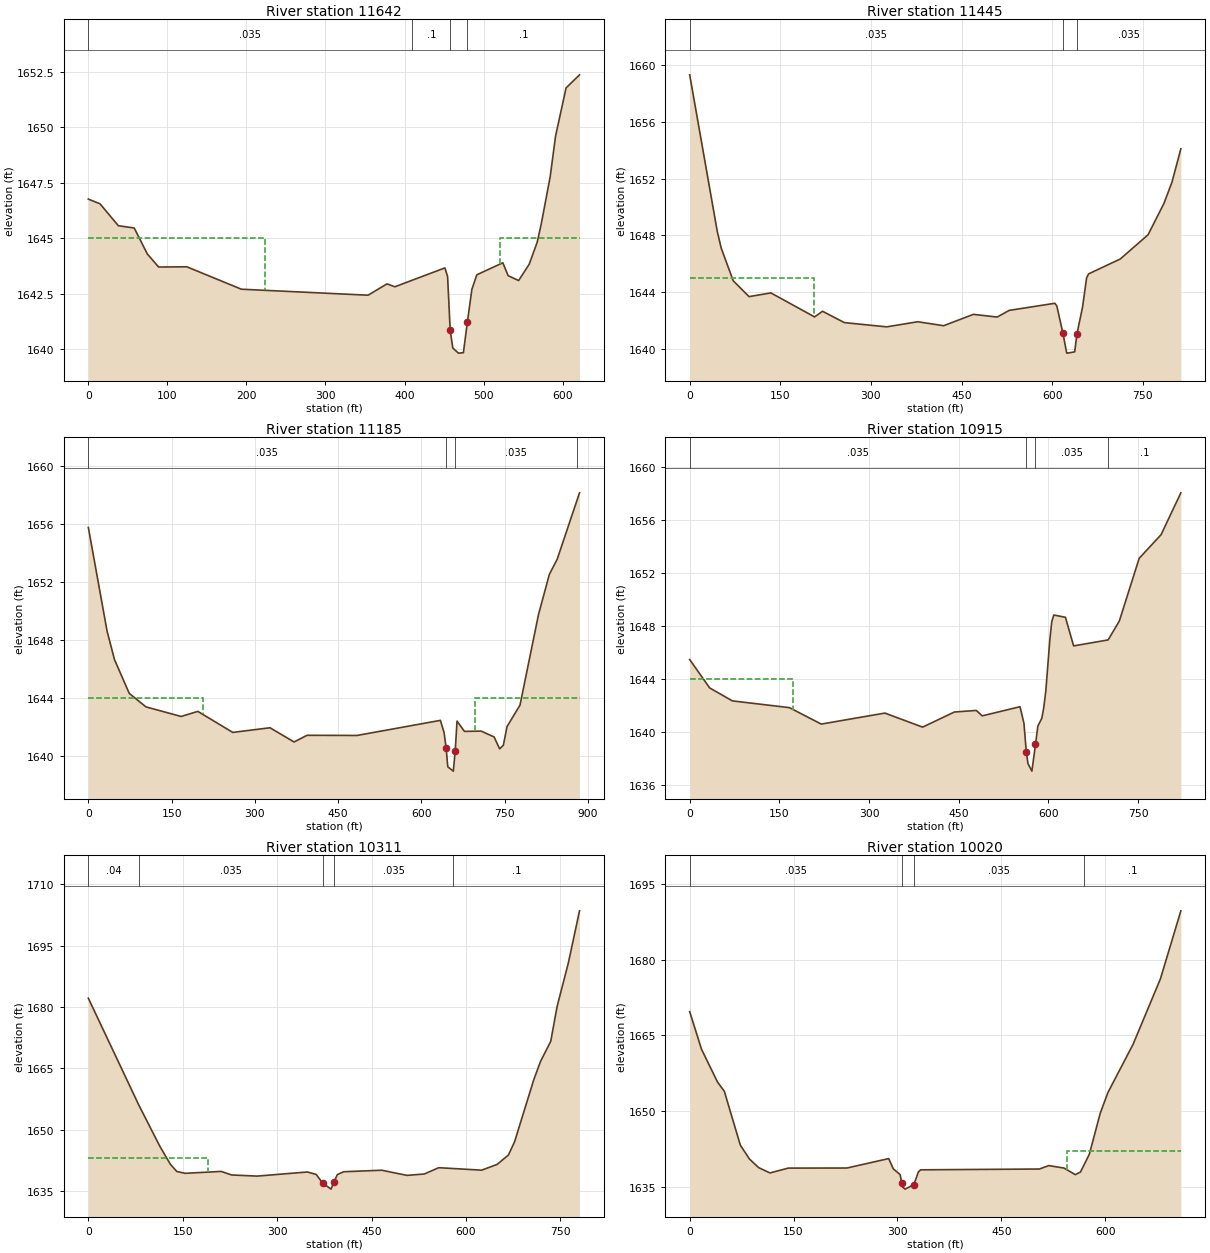
Type RM Length L Ch R = 1 ,11642   ,193.1,196.7,198.1
XS GIS Cut Line= 2
2015390.55582427218183.5580620522015282.28271648  217571.6891041
#Sta/Elev= 30
       0 1646.76    14.7 1646.55      38 1645.56      58 1645.46    74.6 1644.29
    88.9  1643.7   124.6 1643.71   193.6  1642.7   353.9 1642.43   377.8 1642.94
   387.8 1642.81   451.1 1643.66   454.5 1643.27   457.8 1640.85   461.1 1640.05
   468.2 1639.82   474.5 1639.84   479.5 1641.21   485.2 1642.69   491.5 1643.35
   524.4 1643.89   531.1 1643.31   544.4 1643.09   557.8 1643.83   567.8 1644.81
     573 1645.64   584.3 1647.77   591.1  1649.6   604.4 1651.77   621.4 1652.36
#Mann= 4 ,-1 , 0
       0    .035       0     410      .1       0   457.8    .045       0
   479.5      .1       0
#XS Ineff= 2 , 0
             223    1645     521            1645
Permanent Ineff=
       F       F
Bank Sta=457.8,479.5
XS Rating Curve= 0 ,0
Exp/Cntr(USF)=0,0
Exp/Cntr=0.3,0.1

Type RM Length L Ch R = 1 ,11445   ,254.8,260.4,263.2
XS GIS Cut Line= 2
2015536.81252377218342.6667351182015493.61639398217531.009843211
#Sta/Elev= 30
       0 1659.31    45.7 1648.27    52.2  1647.1      72 1644.81    98.2 1643.69
   134.4 1643.95   206.7 1642.26   219.8 1642.66   255.9 1641.86   325.9 1641.56
   377.5 1641.92   420.2 1641.64   469.5 1642.44   508.9 1642.25   528.7 1642.72
   604.2 1643.22   607.5 1643.04   617.4 1641.16   623.9 1639.72   625.4 1639.71
   637.1  1639.8     641 1641.09   650.2 1642.97   656.8 1645.01   660.1 1645.29
   712.6 1646.34   758.6 1648.05   784.9 1650.26   798.1 1651.75   812.8  1654.1
#Mann= 3 ,-1 , 0
       0    .035       0   617.4    .045       0     641    .035       0
#XS Ineff= 2 , 0
             205    1645
Permanent Ineff=
       F       F
Bank Sta=617.4,641
XS Rating Curve= 0 ,0
Exp/Cntr=0.3,0.1

Type RM Length L Ch R = 1 ,11185   ,268.8,270.1,269.4
XS GIS Cut Line= 2
2015641.90657865218349.9122506432015801.12356963217479.704624883
#Sta/Elev= 30
       0 1655.76    33.7 1648.62    47.1 1646.65    73.7 1644.32   103.8 1643.39
   167.1 1642.73   197.2 1643.08   260.1 1641.63   327.2 1641.95   370.6 1640.97
   393.9 1641.43     484 1641.42   634.1 1642.46   640.7 1641.63   644.5 1640.54
   647.4 1639.26   657.4 1638.96   660.8 1640.35   664.1 1642.41   677.4  1641.7
   707.5 1641.72   730.8 1641.32   740.8  1640.5   747.5 1640.74   754.1 1642.03
   777.5 1643.51   810.8 1649.75   830.4 1652.53   844.5 1653.57   884.7 1658.15
#Mann= 4 ,-1 , 0
       0    .035       0   644.5    .045       0   660.8    .035       0
     880      .1       0
#XS Ineff= 2 , 0
             206    1644     696            1644
Permanent Ineff=
       F       F
Bank Sta=644.5,660.8
XS Rating Curve= 0 ,0
Exp/Cntr=0.3,0.1

Type RM Length L Ch R = 1 ,10915   ,598.8,603.8,590.2
XS GIS Cut Line= 2
2015926.04588812218274.7761419622016058.68268584217463.828857224
#Sta/Elev= 30
       0 1645.46    33.4 1643.32    71.4 1642.34   166.9 1641.83   220.1 1640.59
   326.5 1641.42   389.7 1640.36   442.8  1641.5   479.4 1641.62   489.4 1641.21
   552.6  1641.9   559.2 1640.65   563.21638.456     566  1637.6   572.5 1637.04
   578.5 1639.05   582.5 1640.44   589.1 1641.03   592.4 1641.85   595.8  1643.1
   602.4  1646.9   605.7 1648.31   609.1 1648.82   628.6 1648.65   642.3 1646.49
     700 1646.94   718.8 1648.37     752  1653.1   788.6 1654.88   821.7 1658.04
#Mann= 4 ,-1 , 0
       0    .035       0   563.2    .045       0   578.5    .035       0
     700      .1       0
#XS Ineff= 2 , 0
             173    1644
Permanent Ineff=
       F       F
Bank Sta=563.2,578.5
XS Rating Curve= 0 ,0
Exp/Cntr=0.3,0.1

Type RM Length L Ch R = 1 ,10311   ,292.1,291.1,281.8
XS GIS Cut Line= 2
2016277.30641962218444.1696043072016443.09929293217681.522387076
#Sta/Elev= 30
       0 1682.14      80 1656.09   113.6 1645.96   130.4 1641.55   140.5  1639.8
   153.9 1639.34     211 1639.81   227.8 1638.94   268.1 1638.66     348 1639.67
   362.1 1639.07   372.1 1637.01   385.6 1635.48   390.4 1637.19   395.6 1639.03
   405.7 1639.73   466.2  1640.1   506.3 1638.84   533.9 1639.18   556.8 1640.72
   624.9 1640.11   649.7 1641.53   667.6 1643.83   677.3 1647.05   707.9 1662.26
   718.6 1666.71   734.8 1671.62   744.8 1680.06   762.8 1690.79   780.5  1703.5
#Mann= 5 ,-1 , 0
       0     .04       0      80    .035       0   372.1    .045       0
   390.4    .035       0     580      .1       0
#XS Ineff= 2 , 0
             190    1643
Permanent Ineff=
       F       F
Bank Sta=372.1,390.4
XS Rating Curve= 0 ,0
Exp/Cntr(USF)=0,0
Exp/Cntr=0.3,0.1

Type RM Length L Ch R = 1 ,10020   ,318.2,326,327.8
XS GIS Cut Line= 2
2016593.34908437218445.2058097652016522.88711321217739.549892735
#Sta/Elev= 30
       0 1669.73      17 1662.29    40.1 1655.78      50 1653.93    73.1 1643.25
    86.2  1640.5    99.4 1638.79   115.9 1637.72   142.3 1638.68   227.1  1638.7
   287.4 1640.57     294 1638.53   303.9 1637.39   306.1 1635.78   307.2 1634.96
     311 1634.51   323.6 1635.39   330.2 1637.91   333.5 1638.34     505  1638.5
   518.5 1639.18   540.5 1638.69   556.9 1637.38   564.3 1637.91   577.1 1641.45
   592.8 1649.57   603.9 1653.68   640.2 1663.24   679.7 1676.24   709.2 1689.73
#Mann= 4 ,-1 , 0
       0    .035       0   306.1    .045       0   323.6    .035       0
     570      .1       0
#XS Ineff= 2 , 0
                             545            1642
Permanent Ineff=
       F       F
Bank Sta=306.1,323.6
XS Rating Curve= 0 ,0
Exp/Cntr(USF)=0,0
Exp/Cntr=0.3,0.1

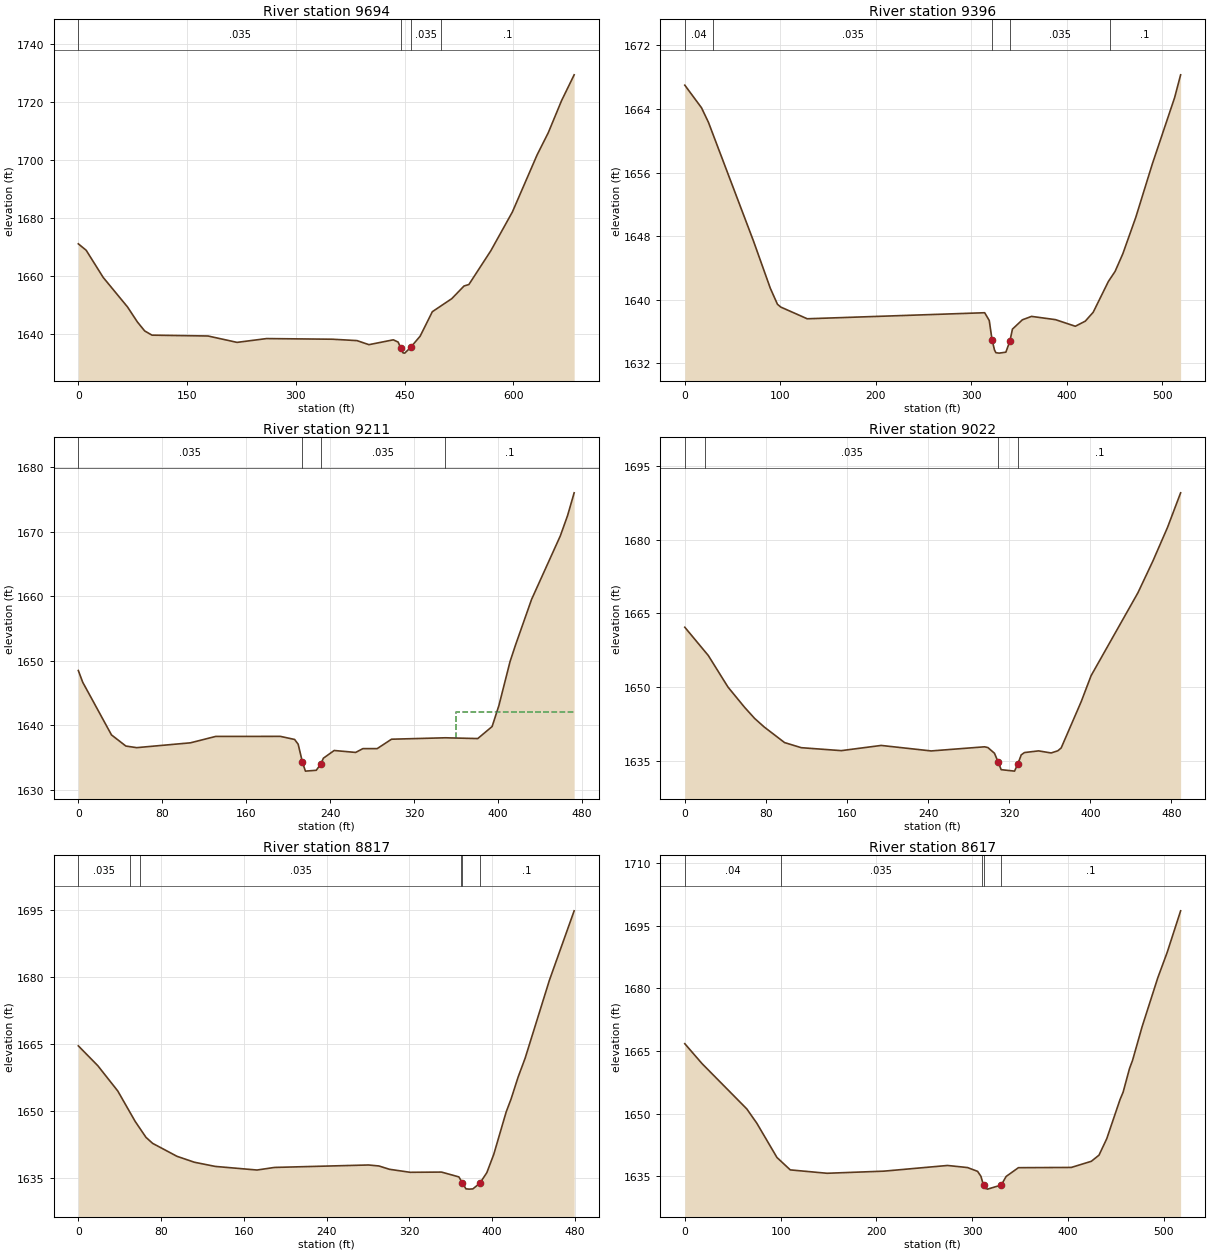
Type RM Length L Ch R = 1 ,9694    ,293.8,297.5,293.3
XS GIS Cut Line= 2
2016648.26797365218461.7850970962016797.48155963217794.468782019
#Sta/Elev= 30
       0 1671.04    10.8 1668.83    34.3 1659.45    67.9 1649.24    81.4  1644.1
    91.5 1640.99   101.6 1639.53   178.9 1639.24   218.9 1637.04   259.6 1638.35
   350.3 1638.13   384.3 1637.65   400.8 1636.25   434.4 1637.92   441.1 1637.14
   444.5 1635.18   447.8 1633.41   450.2 1633.33   458.5 1635.39   471.4 1639.18
   488.2 1647.62   515.1 1652.14   531.9 1656.49   538.6    1657   568.9 1668.67
   598.6 1682.03   632.7 1701.73   648.1 1709.38   666.4 1720.44   683.8 1729.36
#Mann= 4 ,-1 , 0
       0    .035       0   444.5    .045       0   458.5    .035       0
     500      .1       0
Bank Sta=444.5,458.5
XS Rating Curve= 0 ,0
Exp/Cntr(USF)=0,0
Exp/Cntr=0.3,0.1

Type RM Length L Ch R = 1 ,9396    ,184.4,185.4,183.6
XS GIS Cut Line= 3
2016789.95771463218496.6692799392016830.29042938218410.480600418
2016967.47975009218008.899584134
#Sta/Elev= 30
       0    1667    17.5 1664.16    24.8 1662.32    71.9 1647.42    89.6 1641.46
    97.1 1639.44   100.6 1639.09   128.3 1637.62   314.2 1638.38     319  1637.4
   321.9    1635   324.5 1633.69     326 1633.35   329.4  1633.3   336.4 1633.42
   340.6 1634.81   343.3 1636.32   353.7 1637.49   363.3 1637.92   388.4 1637.51
   409.2 1636.68   419.6 1637.32   427.9 1638.44   443.8 1642.31   450.8 1643.57
   458.9 1645.78   472.5 1650.37   489.9 1657.11   513.2 1665.43   519.5  1668.3
#Mann= 5 ,-1 , 0
       0     .04       0      30    .035       0   321.9    .045       0
   340.6    .035       0  445.16      .1       0
Bank Sta=321.9,340.6
XS Rating Curve= 0 ,0
Exp/Cntr=0.3,0.1

Type RM Length L Ch R = 1 ,9211    ,195.1,189.1,182.5
XS GIS Cut Line= 2
2016946.42021639218507.8150861752017081.31423809218054.796345261
#Sta/Elev= 30
       0 1648.49     4.2 1646.67    31.6 1638.51    45.3 1636.78    55.6 1636.53
   106.9 1637.28   130.9 1638.27   192.6 1638.28   206.2  1637.8   209.6 1637.06
   213.7 1634.24   216.5 1632.89   226.8 1633.02   231.3 1634.01   233.6 1634.89
   243.9 1636.09   264.4 1635.79   271.3 1636.38   284.9 1636.38   298.6 1637.84
     350 1638.06   380.8 1637.94   394.5 1639.81     401 1643.09   411.6 1649.89
   416.8 1652.45   432.1 1659.52   459.5 1669.37   466.4 1672.51   472.7 1676.05
#Mann= 4 ,-1 , 0
       0    .035       0   213.7    .045       0   231.3    .035       0
     350      .1       0
#XS Ineff= 2 , 0
                             360            1642
Permanent Ineff=
       F       F
Bank Sta=213.7,231.3
XS Rating Curve= 0 ,0
Exp/Cntr=0.3,0.1

Type RM Length L Ch R = 1 ,9022    ,199.5,205.1,209.7
XS GIS Cut Line= 3
2017209.11082395218588.8929470462017187.02003838218202.548414289
2017234.09234084218112.006779641
#Sta/Elev= 30
       0 1662.15    23.2 1656.39    42.6 1649.97      59 1645.84    68.9 1643.58
    78.4 1641.83    98.4 1638.67   114.9 1637.63   154.3 1637.03   193.7 1638.09
     243 1636.97   295.6 1637.81   298.9 1637.66   305.4  1636.5   309.1 1634.69
     312 1633.16   325.2 1632.86   328.5 1634.34   331.8 1636.17     335 1636.64
   348.9 1636.98   361.3 1636.56   367.9    1637   371.2 1637.58     391 1647.03
   400.7 1652.29   446.9 1669.17   461.7 1675.65   476.1 1682.48     489 1689.51
#Mann= 4 ,-1 , 0
       0     .04       0      20    .035       0   309.1    .045       0
   328.5      .1       0
Bank Sta=309.1,328.5
XS Rating Curve= 0 ,0
Exp/Cntr=0.3,0.1

Type RM Length L Ch R = 1 ,8817    ,196.8,199.9,200.9
XS GIS Cut Line= 2
2017304.87852482218629.5009391082017411.11135671218162.191645296
#Sta/Elev= 30
       0 1664.61    18.8 1660.17    38.1  1654.5    54.9 1647.69    65.4  1644.1
    71.8 1642.76    95.3 1639.86   112.1 1638.53   132.3 1637.59   172.7 1636.78
   189.5 1637.36   280.4 1637.91   290.5 1637.69   300.6 1636.95   320.7 1636.27
     351 1636.32   367.8 1635.24   371.2  1633.9   374.6 1632.56   377.8  1632.5
   381.3 1632.55     388 1633.81   394.8 1636.19   401.5 1640.29   413.5  1649.8
   418.3 1652.74     425 1657.59   431.8 1661.83   455.3 1679.33   479.2 1694.87
#Mann= 6 ,-1 , 0
       0    .035       0      50     .04       0      60    .035       0
     370      .1       0   371.2    .045       0     388      .1       0
Bank Sta=371.2,388
XS Rating Curve= 0 ,0
Exp/Cntr=0.3,0.1

Type RM Length L Ch R = 1 ,8617    ,195.1,179.5,159.5
XS GIS Cut Line= 3
2017449.42917604218659.7293070742017596.46803918218255.264379741
2017592.68686398218168.173349343
#Sta/Elev= 30
       0 1666.75    17.9    1662    64.7 1651.12    75.2 1647.68    96.2 1639.47
   110.1  1636.5   148.5 1635.69   207.9  1636.2   274.2 1637.56   295.1 1637.06
   305.6 1636.15   309.1 1634.95   311.8 1632.79   312.6 1632.16   316.1 1631.89
   330.3 1632.88   335.4 1634.93   348.2 1637.03   403.4 1637.09   424.3 1638.56
   432.3 1640.03   440.4 1643.98   454.3 1653.39   457.5 1655.14   464.1 1660.76
   467.3 1662.74   477.2 1670.75   493.6  1682.5   503.5 1688.66   517.5  1698.6
#Mann= 5 ,-1 , 0
       0     .04       0     100    .035       0     310      .1       0
   311.8    .045       0   330.3      .1       0
Bank Sta=311.8,330.3
XS Rating Curve= 0 ,0
Exp/Cntr=0.3,0.1

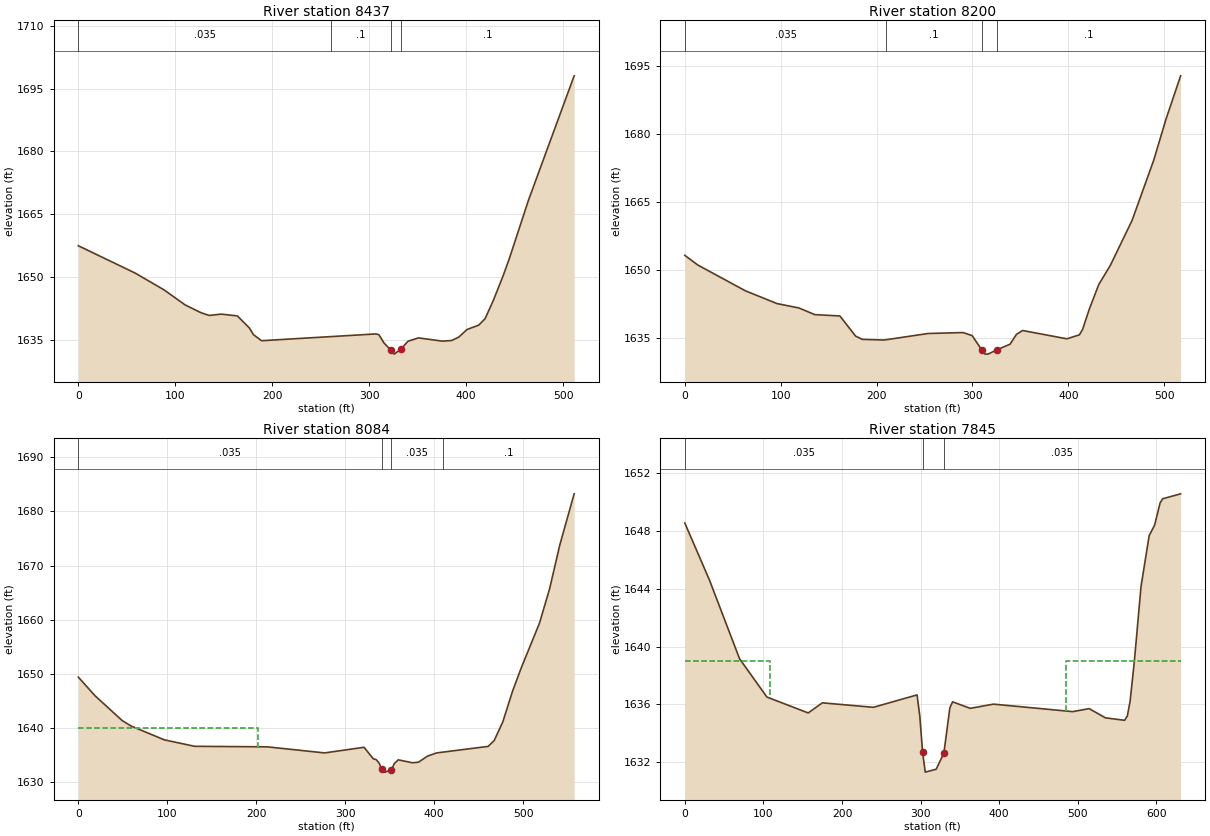
Type RM Length L Ch R = 1 ,8437    ,225.4,237.4,248.7
XS GIS Cut Line= 4
2017867.11787211218598.6322863262017864.66248148218498.372489491
2017668.27203395218244.5710278132017652.07317733218155.954556555
#Sta/Elev= 30
       0 1657.49    58.8 1650.95    88.4 1646.96   110.1 1643.38   126.7 1641.49
     135 1640.86   147.4 1641.18     164 1640.75   176.5 1637.84   180.6 1636.27
   188.9 1634.83   306.9 1636.45   309.9 1636.28   315.2  1634.3   322.11632.617
   325.8 1631.63   332.9 1632.88   339.9  1634.7   350.7 1635.51   375.6 1634.72
   384.9 1634.88   392.2 1635.67   400.7 1637.49   412.9 1638.55   419.4 1640.07
   427.9 1644.41   437.9 1650.23   444.6 1654.53   464.2 1668.36   511.3 1698.04
#Mann= 4 ,-1 , 0
       0    .035       0  260.29      .1       0   322.1    .045       0
   332.9      .1       0
Bank Sta=322.1,332.9
XS Rating Curve= 0 ,0
Exp/Cntr=0.3,0.1

Type RM Length L Ch R = 1 ,8200    ,121.7,116.1,109.9
XS GIS Cut Line= 3
2017915.72652482218583.2122077982017941.45719524218164.427548634
     2017894.518218078.810097969
#Sta/Elev= 30
       0 1653.22    13.6 1651.08    63.2 1645.41    96.1  1642.6   119.1 1641.63
   135.5 1640.17   161.8 1639.87   178.2 1635.43   185.2 1634.72   207.8 1634.57
   253.8 1636.01   290.3 1636.22   299.8 1635.54   309.7 1632.41     313 1631.49
   316.3 1631.47   325.3  1632.4   339.3 1633.66   345.9 1635.81   352.4 1636.67
   398.5 1634.84   411.6 1635.72   414.9 1636.88   421.7 1641.22   431.8 1646.78
   443.9 1651.01   466.6 1660.92   489.1 1674.13   501.9 1683.16   517.2 1692.73
#Mann= 4 ,-1 , 0
       0    .035       0     210      .1       0   309.7    .045       0
   325.3      .1       0
Bank Sta=309.7,325.3
XS Rating Curve= 0 ,0
Exp/Cntr=0.3,0.1

Type RM Length L Ch R = 1 ,8084    ,227.2,239,249.4
XS GIS Cut Line= 2
2018137.31597225218567.5972733252017990.46742161218029.832442037
#Sta/Elev= 30
       0 1649.38    18.6 1645.97    49.2 1641.37    59.4 1640.34    96.8 1637.79
   130.8  1636.6   212.4  1636.5   276.9 1635.38   321.3 1636.42   331.5 1634.31
   334.9 1634.14   338.3 1633.47     341 1632.43   345.1 1631.83   352.1 1632.29
   355.3 1633.41   359.7  1634.1   375.7 1633.56   382.5 1633.67   392.7  1634.8
   402.9 1635.38   460.7 1636.58   467.5 1637.64   477.3 1641.12   488.2 1646.77
   498.1 1651.13   518.5 1659.34   529.9 1665.71   541.4 1673.82   557.5 1683.24
#Mann= 4 ,-1 , 0
       0    .035       0     341    .045       0   352.1    .035       0
     410      .1       0
#XS Ineff= 2 , 0
             202    1640
Permanent Ineff=
       F       F
Bank Sta=341,352.1
XS Rating Curve= 0 ,0
Exp/Cntr(USF)=0,0
Exp/Cntr=0.3,0.1

Type RM Length L Ch R = 1 ,7845    ,515.6,511.2,500.4
XS GIS Cut Line= 2
2018166.73384521218563.0412851672018373.97493685217967.223146704
#Sta/Elev= 30
       0 1648.57    31.5  1644.6    69.7 1639.16   104.5 1636.51     157 1635.41
     175 1636.11   239.9  1635.8   295.5 1636.66     299 1635.18   302.5 1632.72
   305.9 1631.31   319.8 1631.51   329.6 1632.62   337.2 1635.76   340.7 1636.18
   363.1 1635.73   392.8 1636.02   493.5  1635.5   514.4 1635.71   535.2 1635.07
   559.5  1634.9     563  1635.2   566.5 1636.21   571.9 1638.96   580.4 1644.16
   590.8  1647.7   597.7 1648.42   604.7 1649.96   608.1 1650.25   630.8 1650.59
#Mann= 3 ,-1 , 0
       0    .035       0   302.5    .045       0   329.6    .035       0
#XS Ineff= 2 , 0
             108    1639     485            1639
Permanent Ineff=
       F       F
Bank Sta=302.5,329.6
XS Rating Curve= 0 ,0
Exp/Cntr(USF)=0,0
Exp/Cntr=0.3,0.1