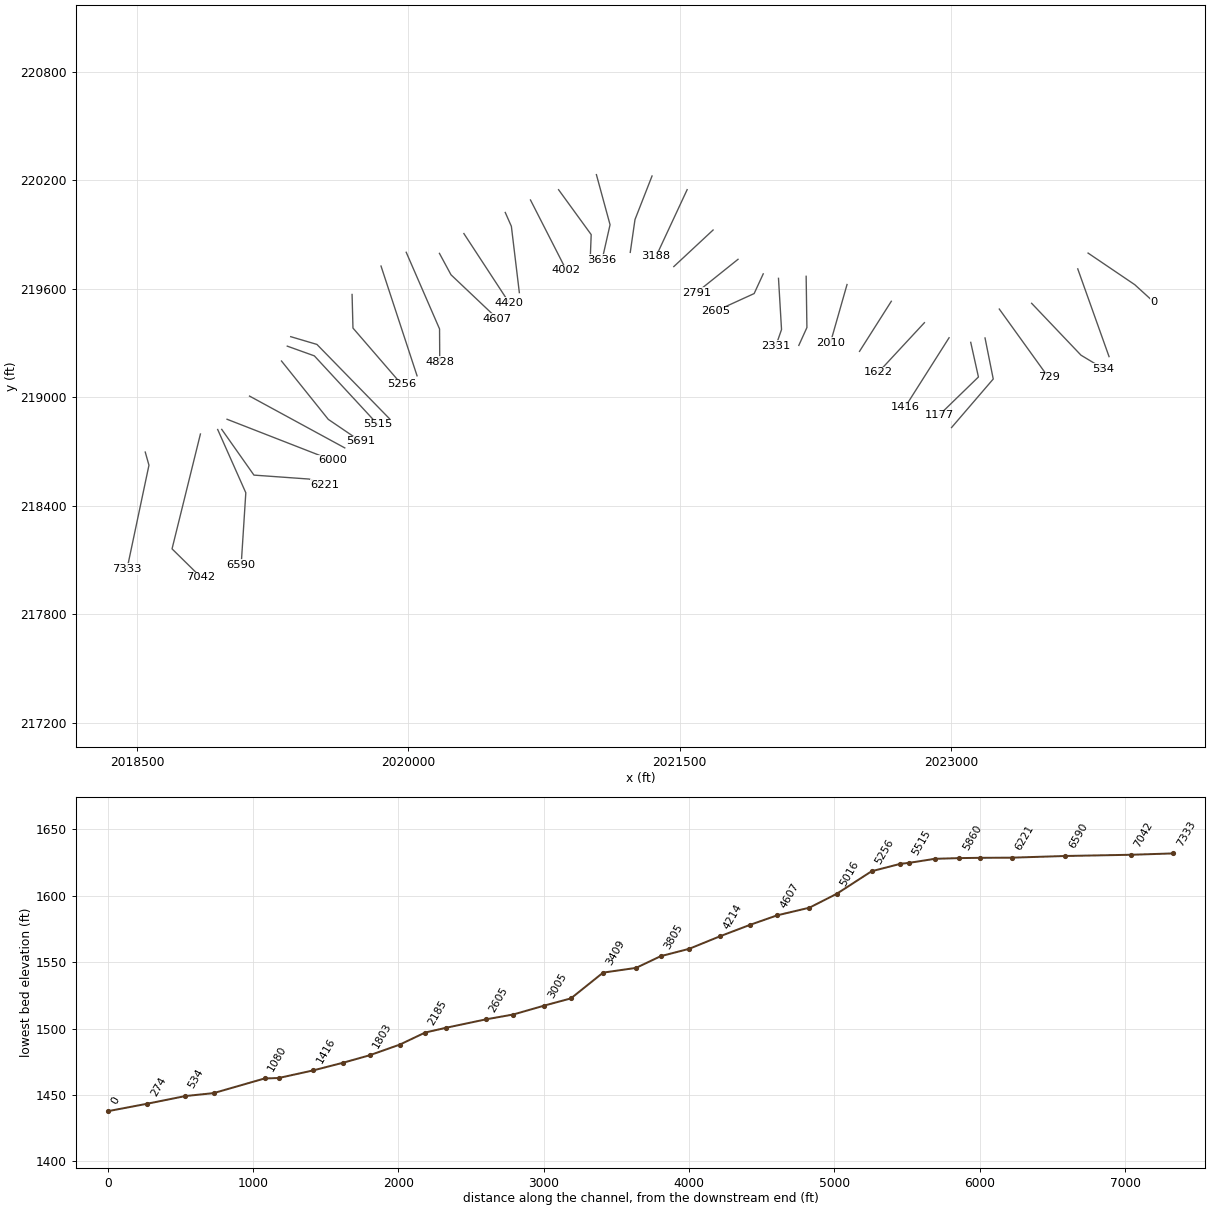
HEC-RAS study WOLFCK_A.prj: WOLFCK_A

--- WOLFCK_A.g01 (geometry) --- (continued)

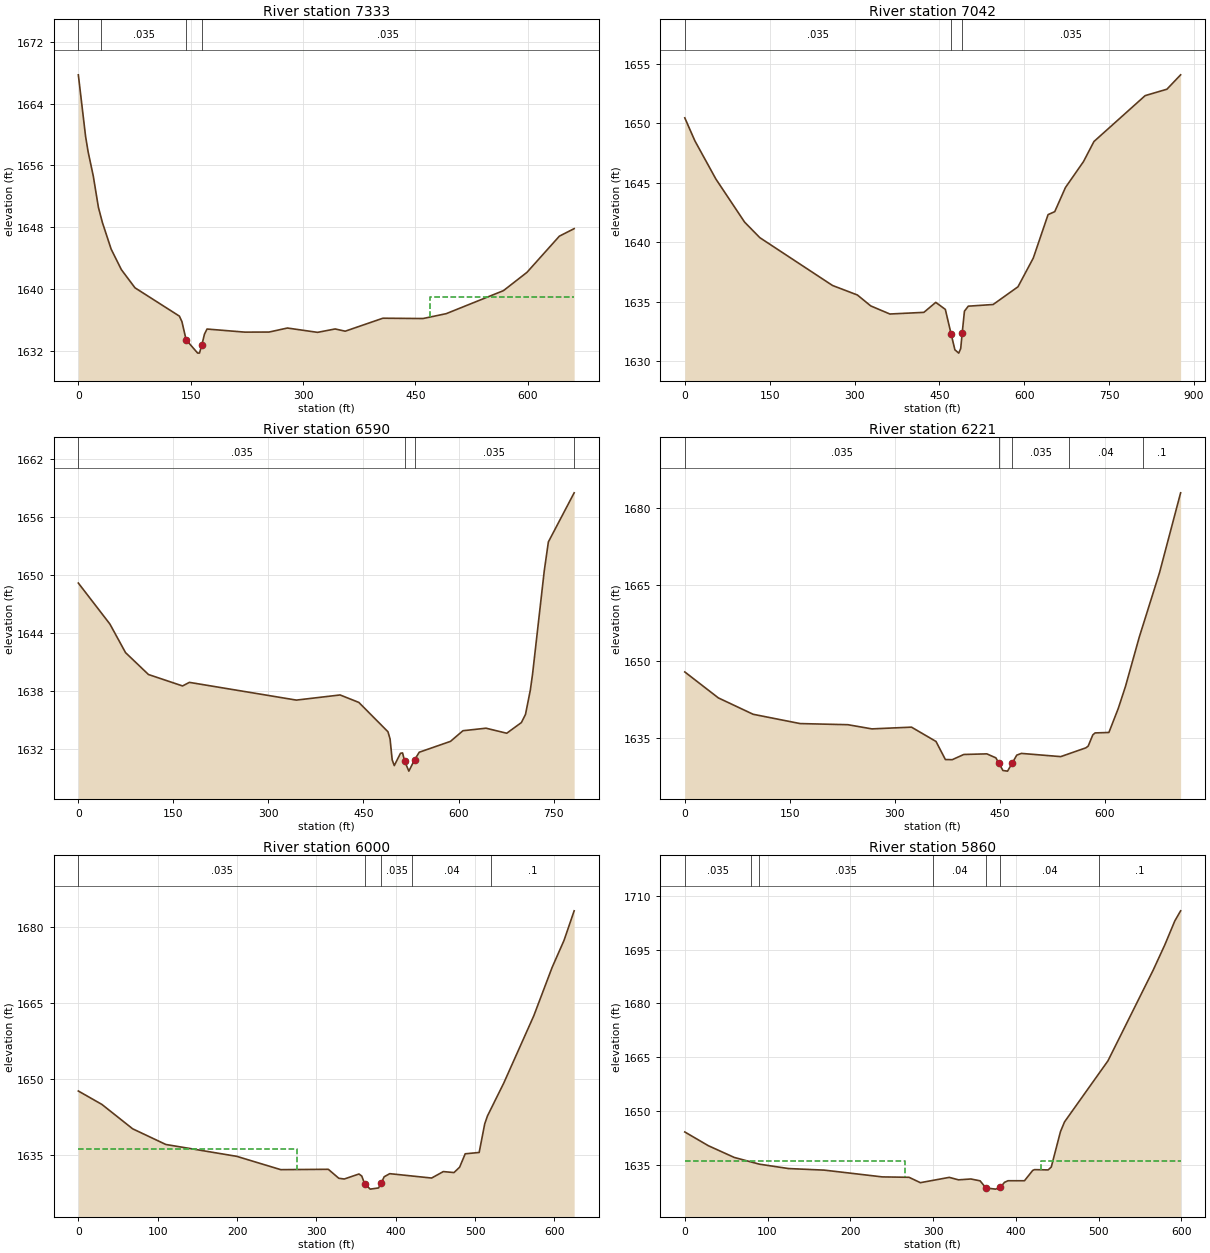
Type RM Length L Ch R = 1 ,7333    ,290.7,291.1,288.4
XS GIS Cut Line= 3
 2018545.8745834218696.8305384192018566.39145148218624.088915254
2018445.15541287218050.549194143
#Sta/Elev= 30
       0 1667.73     9.7 1659.74    13.1 1657.75    19.9 1654.65    26.8 1650.57
    32.2 1648.58    43.8 1645.16    57.4 1642.51    75.6 1640.15   134.9 1636.48
   138.3 1635.76   143.9 1633.41   159.3 1631.69   161.7  1631.7     165  1632.8
   168.4 1634.16   171.8 1634.81   222.1 1634.41   254.6 1634.42   279.1 1634.94
   319.3 1634.38   342.8 1634.82   356.2 1634.53   406.5 1636.21   460.1 1636.17
     491  1636.8   567.4 1639.78   598.8 1642.15   642.1 1646.84   661.8 1647.81
#Mann= 4 ,-1 , 0
       0     .04       0      30    .035       0   143.9    .045       0
     165    .035       0
#XS Ineff= 2 , 0
                             469            1639
Permanent Ineff=
       F       F
Bank Sta=143.9,165
XS Rating Curve= 0 ,0
Exp/Cntr(USF)=0,0
Exp/Cntr=0.3,0.1

Type RM Length L Ch R = 1 ,7042    ,444.6,452.7,453.4
XS GIS Cut Line= 3
2018850.82984975218796.6171240442018694.00775446218161.822458736
2018852.70138668218005.836230929
#Sta/Elev= 30
       0 1650.46    17.8 1648.53      55 1645.31   105.7 1641.69   132.7 1640.38
   261.1 1636.36   305.1 1635.56   328.7 1634.64   362.5 1633.96   422.6  1634.1
   443.6 1634.94   460.5 1634.35   470.81632.267   477.4 1630.95   484.2 1630.67
   487.7 1631.06   490.4  1632.4   494.3  1634.2   501.1 1634.62     545 1634.76
   588.9 1636.25     616 1638.67   642.1 1642.32   653.9 1642.57   672.8  1644.6
   704.7 1646.78   723.2 1648.47   813.7 1652.33   852.2 1652.87   876.4 1654.08
#Mann= 3 ,-1 , 0
       0    .035       0   470.8    .045       0   490.4    .035       0
Bank Sta=470.8,490.4
XS Rating Curve= 0 ,0
Exp/Cntr(USF)=0,0
Exp/Cntr=0.3,0.1

Type RM Length L Ch R = 1 ,6590    ,339.5,368.6,395.4
XS GIS Cut Line= 3
2018946.27175474 218821.417490172019101.72671613218471.795887377
2019076.08706595218072.764544142
#Sta/Elev= 30
       0 1649.16    49.8 1644.93    74.5 1641.98   110.7 1639.72   164.5 1638.54
   175.3 1638.91   344.1 1637.08   413.1 1637.61   442.7 1636.84   488.7 1633.81
     492 1633.06   495.3 1630.92   498.6 1630.32   508.4 1631.59   511.7 1631.63
     515 1630.78   521.6 1629.75   530.6 1630.91     538  1631.7   587.3 1632.82
     607 1633.92   643.4 1634.18   676.1 1633.66   699.2 1634.76   705.7  1635.6
   713.3  1638.1   716.8 1639.73   735.3 1650.41   741.8  1653.4   782.5 1658.47
#Mann= 4 ,-1 , 0
       0    .035       0     515    .045       0   530.6    .035       0
  782.48     .04       0
Bank Sta=515,530.6
XS Rating Curve= 0 ,0
Exp/Cntr=0.3,0.1

Type RM Length L Ch R = 1 ,6221    ,224.1,221.3,210.2
XS GIS Cut Line= 4
2018968.64641035218822.1077783152019146.62126731218569.457826004
2019451.41453332218547.6169524392019539.85129024218517.507440794
#Sta/Elev= 30
       0 1647.91    47.9 1642.83    97.6 1639.62   164.7  1637.8   232.9 1637.58
   267.1 1636.76   323.7  1637.1   358.7  1634.3   372.1 1630.76   381.9 1630.73
   398.4 1631.75   431.3 1631.87   444.2 1631.09   448.1 1630.13   454.3 1628.61
   460.9 1628.49   467.5 1630.06     474 1631.62   480.6 1631.96   536.8 1631.33
   572.7 1633.05     576 1633.39   582.6 1635.58   585.9 1635.97   605.6 1636.06
     619 1640.78   629.2 1645.05   648.9 1654.71   677.9 1667.37     708 1682.98
#Mann= 5 ,-1 , 0
       0    .035       0   448.1    .045       0   467.5    .035       0
  549.04     .04       0  654.62      .1       0
Bank Sta=448.1,467.5
XS Rating Curve= 0 ,0
Exp/Cntr=0.3,0.1

Type RM Length L Ch R = 1 ,6000    ,141.8,139.3,135.1
XS GIS Cut Line= 2
2018998.06872826218878.0858750432019580.18721203218651.132880357
#Sta/Elev= 30
       0 1647.66    29.7 1645.02    68.5 1640.22   110.3 1637.14   199.6 1634.81
   255.1 1632.19     315 1632.26   328.2  1630.5   335.1 1630.35   353.7 1631.34
   357.2 1630.92   360.7 1629.43   367.8 1628.36   378.3 1628.59   381.9 1629.63
   385.4 1630.79   392.4  1631.4   445.2 1630.54   459.9 1631.81   473.4 1631.62
   480.5 1632.68   487.5 1635.31   505.1 1635.57   512.1  1641.2   515.6 1642.77
     536 1649.19     574 1662.48     597 1671.96     612 1677.27   624.8  1683.1
#Mann= 5 ,-1 , 0
       0    .035       0   360.7    .045       0   381.9    .035       0
     420     .04       0     520      .1       0
#XS Ineff= 2 , 0
          274.97  1636.3
Permanent Ineff=
       F       F
Bank Sta=360.7,381.9
XS Rating Curve= 0 ,0
Exp/Cntr=0.3,0.1

Type RM Length L Ch R = 1 ,5860    ,176.3,169.6,158.4
XS GIS Cut Line= 2
2019122.31758129219006.1865325432019648.64582987218719.837860854
#Sta/Elev= 30
       0 1644.11    28.5 1640.27    59.8    1637    90.2 1635.12   125.4  1633.9
   168.6 1633.46   238.8 1631.57     271 1631.46   284.7 1629.96   319.6 1631.44
   330.8 1630.75   345.7 1630.99   356.9 1630.47   363.9 1628.48   375.6 1628.16
   381.5 1628.67   386.3 1630.05   390.6  1630.5   410.5  1630.5   420.4 1633.37
   422.6  1633.6   439.1 1633.52   442.9 1634.34     454 1644.21   458.9 1646.92
   511.4 1663.96   566.1  1689.3   579.9 1696.21   592.2    1703   599.2 1705.81
#Mann= 7 ,-1 , 0
       0    .035       0      80     .04       0      90    .035       0
     300     .04       0   363.9    .045       0   381.5     .04       0
     500      .1       0
#XS Ineff= 2 , 0
             266    1636     430            1636
Permanent Ineff=
       F       F
Bank Sta=363.9,381.5
XS Rating Curve= 0 ,0
Exp/Cntr(USF)=0,0
Exp/Cntr=0.3,0.1

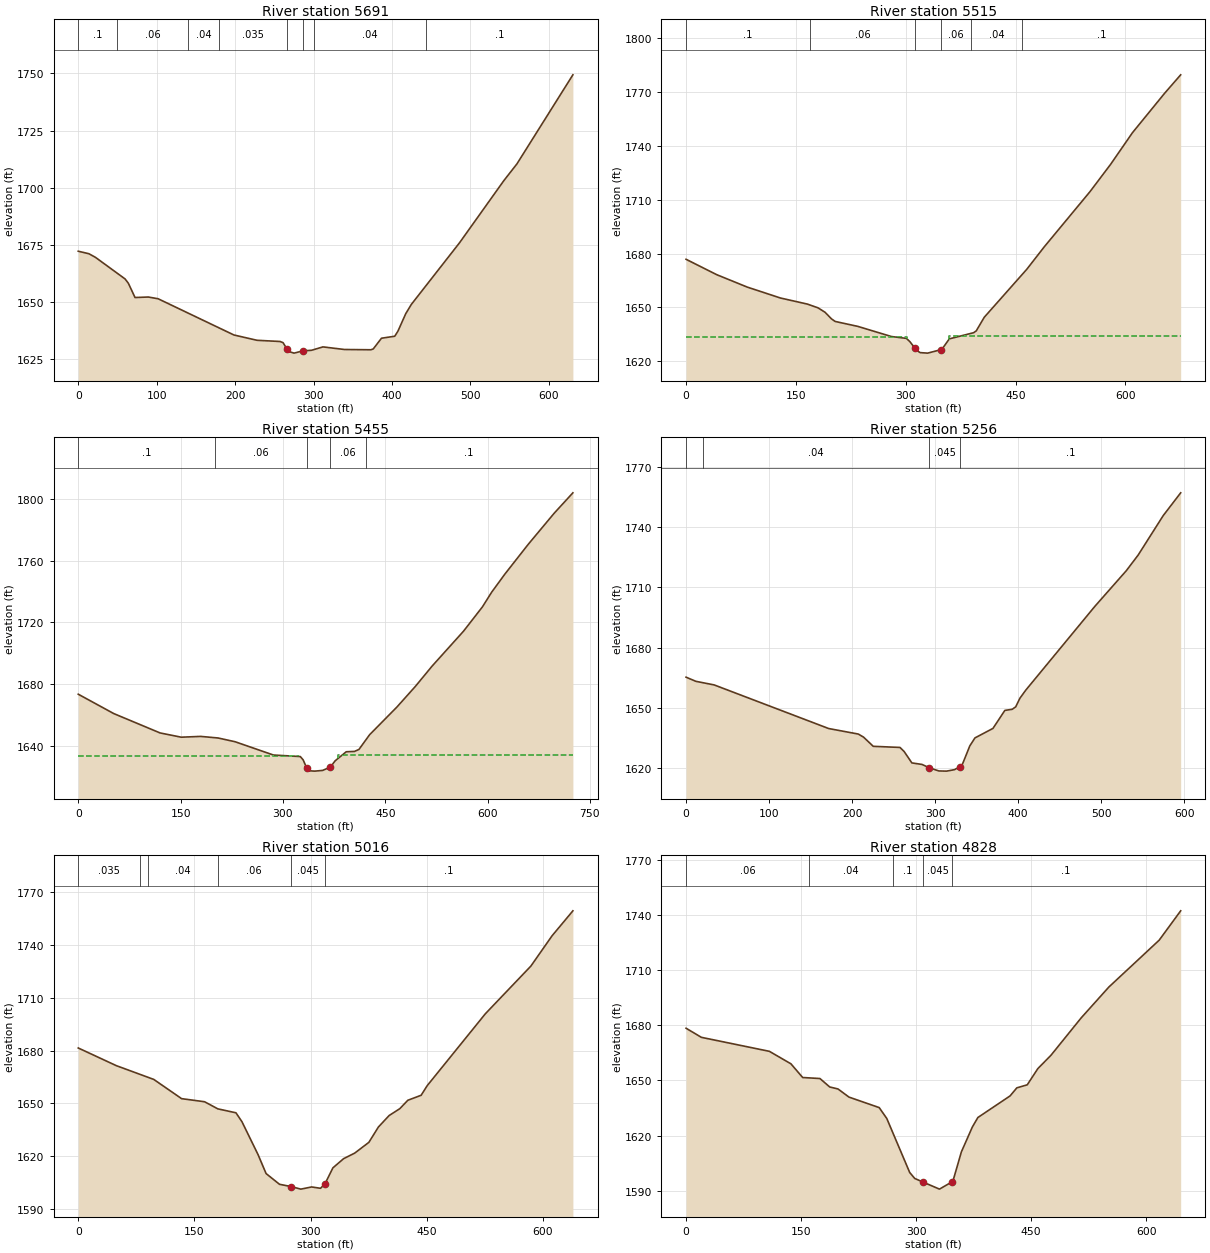
Type RM Length L Ch R = 1 ,5691    ,173.4,175.5,176.2
XS GIS Cut Line= 3
2019298.96713421219199.9599516842019557.31180534218877.708967163
2019737.47322074218755.335175573
#Sta/Elev= 30
       0  1672.2    13.5 1671.11    21.9 1669.53    59.7 1660.07    63.9 1658.17
    72.4 1651.94    89.2 1652.16   101.8 1651.41   198.5 1635.55   227.9 1633.23
   257.4  1632.7   261.2 1632.18   265.8 1629.58   270.6 1628.09   275.2 1627.61
     287 1628.63   297.5 1628.85     312 1630.34   339.5  1629.2   373.3 1629.08
   376.2 1629.45   386.7 1634.13   403.6    1635   407.7 1637.24   417.7 1644.91
   424.8 1648.94   486.2 1675.88   542.8 1703.12   559.4  1710.4   630.8 1749.39
#Mann= 8 ,-1 , 0
       0      .1       0      50     .06       0     140     .04       0
     180    .035       0   265.8    .045       0     287    .035       0
     300     .04       0  443.02      .1       0
Bank Sta=265.8,287
XS Rating Curve= 0 ,0
Exp/Cntr(USF)=0,0
Exp/Cntr=0.5,0.3

Type RM Length L Ch R = 1 ,5515    ,58.8,60.4,60.5
XS GIS Cut Line= 3
 2019330.9202909219282.222333809 2019480.4882584219228.513836389
2019831.29312763218849.155082459
#Sta/Elev= 30
       0 1676.83    41.8 1668.28    83.6 1661.35   128.9 1655.28   165.7 1651.89
   180.2 1649.81   189.8 1647.35   198.7 1643.64   203.7 1642.22   234.5 1639.49
   280.4 1633.84     301 1632.79   305.8 1630.95   312.9 1627.22   315.5 1625.95
   319.8 1624.87     330 1624.59   347.7 1626.47   350.7 1627.43   359.6 1632.53
   392.8 1635.96   396.4    1637   407.3 1644.55   465.3 1671.22   489.4 1683.83
   551.8 1714.52   579.9  1729.7   609.8 1747.33   653.7 1769.27   675.6 1779.52
#Mann= 6 ,-1 , 0
       0      .1       0  168.92     .06       0   312.9    .045       0
   347.7     .06       0  388.92     .04       0  458.92      .1       0
#XS Ineff= 2 , 0
           301.9  1633.8   358.7            1634
Permanent Ineff=
       F       F
Bank Sta=312.9,347.7
XS Rating Curve= 0 ,0
Exp/Cntr(USF)=0,0
Exp/Cntr=0.5,0.3

Type RM Length L Ch R = 1 ,5455    ,200,198.5,196.4
XS GIS Cut Line= 3
2019349.95621404219334.5711224342019494.76520075219291.740295377
2019895.87929541218881.108239152
#Sta/Elev= 30
       0 1673.58      52 1661.07   119.9 1648.55     151 1645.79   179.4 1646.31
   204.9 1645.28   229.8 1642.87   286.1 1634.26   325.5 1633.28   329.6 1631.15
   334.8 1625.88   339.5 1624.04   346.4 1623.86   358.2 1624.31   369.6 1626.52
   376.6 1630.56   392.8 1636.38   404.8 1636.59   411.4 1637.87     427 1647.38
   467.1 1665.31     494 1678.58   518.7 1691.79   564.6 1714.28   592.4 1730.04
   605.9 1739.51   625.4 1751.29   659.6  1770.5   697.6 1790.59     725 1803.77
#Mann= 5 ,-1 , 0
       0      .1       0  201.01     .06       0   334.8    .045       0
   369.6     .06       0  421.01      .1       0
#XS Ineff= 2 , 0
           323.8  1633.8   380.6            1634
Permanent Ineff=
       F       F
Bank Sta=334.8,369.6
XS Rating Curve= 0 ,0
Exp/Cntr(USF)=0,0
Exp/Cntr=0.5,0.3

Type RM Length L Ch R = 1 ,5256    ,247.3,240.6,220.5
XS GIS Cut Line= 3
2019689.03928089219567.8406016252019693.96253929219382.160930274
2019962.00084847  219071.8505935
#Sta/Elev= 30
       0 1665.18    11.8 1663.11    33.9 1661.31   171.8 1639.53   207.5 1636.77
   213.8 1635.24   225.5 1630.65   257.7 1630.09   262.7 1628.04     272 1622.37
   284.3 1621.59   292.8 1619.96   304.5 1618.35   313.8 1618.26   323.4 1618.99
   330.1 1620.55     333  1621.8   341.8 1630.88     348 1634.85   369.7  1639.6
     384 1648.59   392.9 1649.14   397.1 1650.39   402.2 1654.71   409.2  1658.7
   492.4 1700.54   530.2 1718.31   544.5 1726.12   574.8  1745.9   595.8 1757.25
#Mann= 4 ,-1 , 0
       0     .06       0      20     .04       0   292.8    .045       0
   330.1      .1       0
Bank Sta=292.8,330.1
XS Rating Curve= 0 ,0
Exp/Cntr=0.3,0.1

Type RM Length L Ch R = 1 ,5016    ,184.2,187.4,189.3
XS GIS Cut Line= 2
2019848.97888513219724.9571553042020048.16060098 219118.20129256
#Sta/Elev= 30
       0 1681.52    49.1 1671.48    97.5 1663.64   133.4 1652.71   163.1 1650.94
   180.2  1646.9   203.6 1644.66   211.4 1639.54   232.1 1620.89   242.5  1610.1
   259.8    1604   274.4 1602.74   287.4 1601.25   301.2 1602.48   312.8 1601.73
   318.5 1604.23   328.8 1613.37   342.6 1618.58     357 1621.76   375.2 1627.86
   387.5 1636.57   401.3 1643.09   415.2 1647.03   425.5 1651.79   442.7 1654.64
   450.5 1660.09   525.6 1700.99   584.4 1728.12   611.7 1745.32   638.6 1759.53
#Mann= 6 ,-1 , 0
       0    .035       0      80     .06       0      90     .04       0
     180     .06       0   274.4    .045       0   318.5      .1       0
Bank Sta=274.4,318.5
XS Rating Curve= 0 ,0
Exp/Cntr(USF)=0,0
Exp/Cntr=0.3,0.1

Type RM Length L Ch R = 1 ,4828    ,208.8,221.3,228.9
XS GIS Cut Line= 3
2019988.29095228219800.9455555712020172.50525596219377.252657109
2020173.65659536219194.189692828
#Sta/Elev= 30
       0 1678.31      20 1673.36   108.7 1665.75   136.8 1658.96   152.1 1651.52
   174.6 1650.97   187.4 1646.37   198.1 1645.31   212.5 1640.87   251.9 1635.17
   261.8 1629.25   291.7 1599.88   298.3 1596.64   309.5 1594.61   330.5 1590.85
   346.6 1594.74   346.6 1594.76   348.4  1595.7   359.1 1611.12   373.4 1624.62
   380.6 1629.78   422.6 1641.52   431.4  1645.9     445 1647.56   458.8 1656.36
   475.9  1663.6   515.3 1683.92   551.4 1700.69     617 1726.15   645.1 1742.13
#Mann= 5 ,-1 , 0
       0     .06       0     160     .04       0     270      .1       0
   309.5    .045       0   346.6      .1       0
Bank Sta=309.5,346.6
XS Rating Curve= 0 ,0
Exp/Cntr(USF)=0,0
Exp/Cntr=0.3,0.1

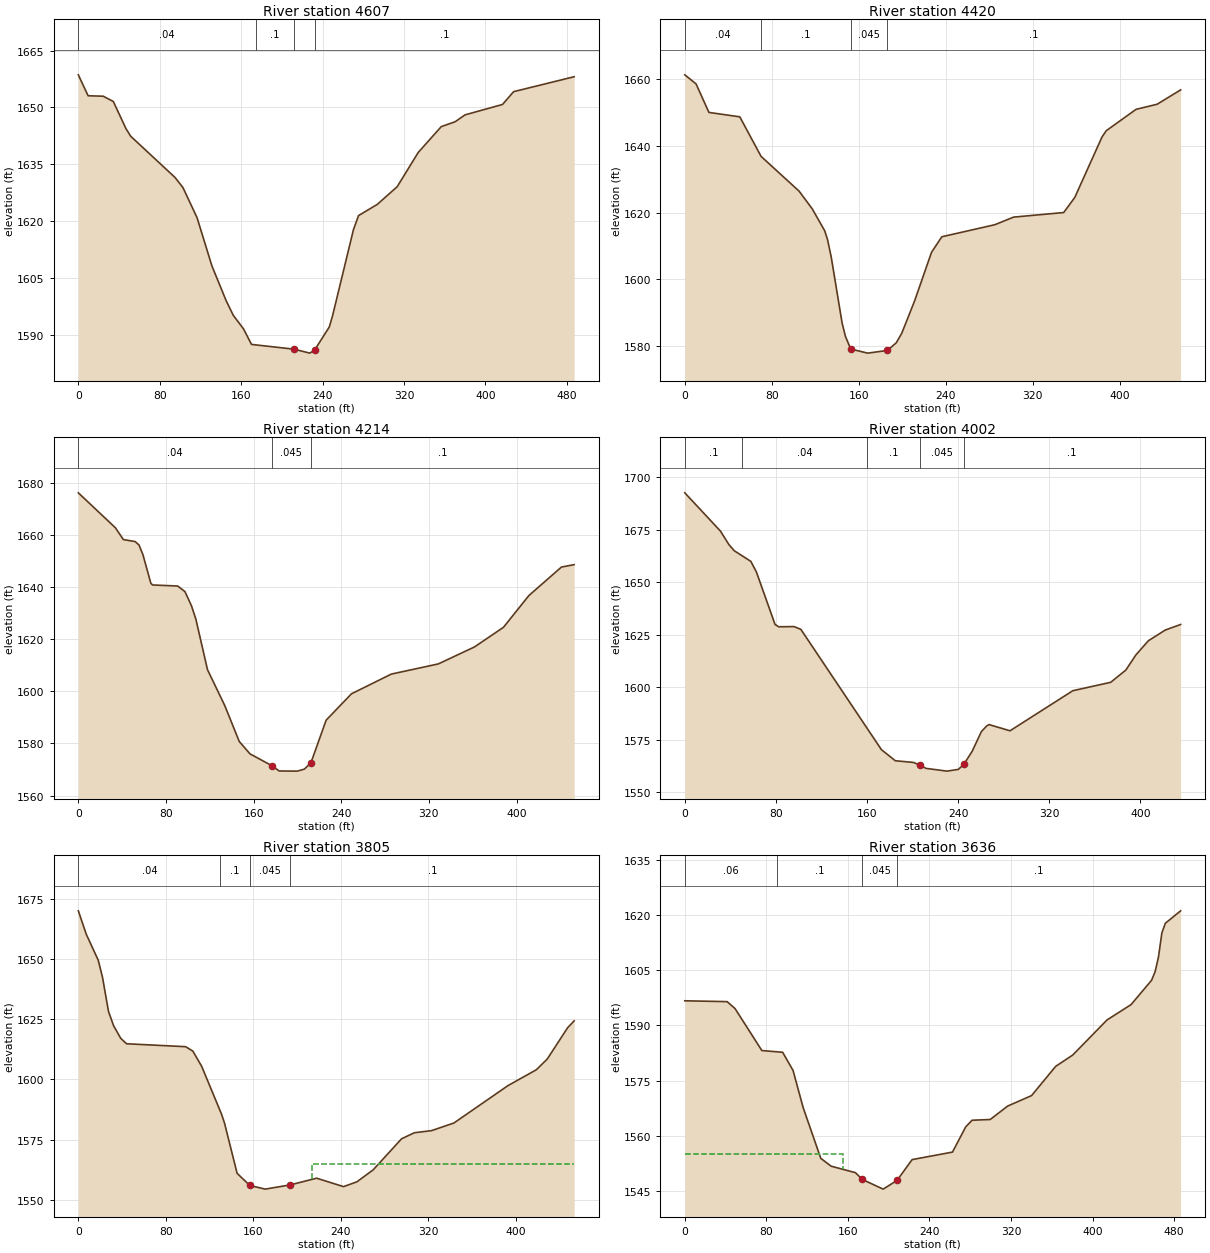
Type RM Length L Ch R = 1 ,4607    ,189.5,186.9,174
XS GIS Cut Line= 3
2020171.90298248219794.9647208022020235.82892285219676.600900588
2020491.95845418219433.959188228
#Sta/Elev= 30
       0 1658.63     9.6  1653.1    24.5 1652.98    34.4 1651.58    46.8 1644.43
    51.4 1642.43      95 1631.53   102.8 1628.86   116.7 1620.89   131.3 1608.15
   145.3 1598.96   152.3  1595.1   162.4  1591.5   170.2 1587.42   212.1 1586.16
   227.5 1585.12   232.3 1585.97   246.6    1592   249.8 1594.92   270.4 1617.74
   275.4 1621.45   293.9 1624.42   313.4 1629.09   334.1 1638.14   356.7 1644.95
   370.3 1646.23   380.1 1648.06   416.9  1650.8   427.8 1654.18   487.3 1658.13
#Mann= 4 ,-1 , 0
       0     .04       0  174.52      .1       0   212.1    .045       0
   232.3      .1       0
Bank Sta=212.1,232.3
XS Rating Curve= 0 ,0
Exp/Cntr=0.3,0.1

Type RM Length L Ch R = 1 ,4420    ,214.9,206.2,188.6
XS GIS Cut Line= 2
2020307.02780054219904.3670175252020556.77877538  219522.5809398
#Sta/Elev= 30
       0 1661.24    10.4 1658.51    22.2 1649.99    50.6 1648.67    70.2 1636.83
   105.2 1626.42   117.3 1621.12   128.7 1614.58   131.3 1611.98   134.7 1606.77
   144.7 1587.04   147.8 1582.97   152.6 1579.23   152.6 1579.21   168.2 1577.96
   186.4 1578.76   194.6 1581.06   199.6 1583.89   211.4 1593.55     227 1608.12
   236.5 1612.78   285.3 1616.39   302.5 1618.66   348.6 1620.03   358.8 1624.53
   383.9 1642.66   387.8 1644.52   415.2 1650.91   434.6 1652.44   456.2 1656.73
#Mann= 4 ,-1 , 0
       0     .04       0      70      .1       0   152.6    .045       0
   186.4      .1       0
Bank Sta=152.6,186.4
XS Rating Curve= 0 ,0
Exp/Cntr=0.3,0.1

Type RM Length L Ch R = 1 ,4214    ,198.8,212,218.9
XS GIS Cut Line= 3
2020535.66032642220021.0248662932020569.47668264219944.351242196
2020613.46011906219578.176524499
#Sta/Elev= 30
       0 1676.13    33.9  1662.7    41.1  1658.2    51.9 1657.43    55.4  1656.1
      59 1652.38    66.2 1641.43    67.8 1640.78    90.7 1640.38    97.3 1638.26
   103.2 1632.88   107.3 1627.68   117.9  1608.3   133.7  1594.5   146.9 1580.74
   156.8 1575.97   176.6 1571.49   183.3 1569.44   199.8 1569.38   206.4 1570.16
   212.3 1572.56   226.2 1588.92   249.3 1599.03   285.7  1606.6   328.6  1610.5
   361.7 1617.03   388.1 1624.56   411.3 1636.74     441 1647.66   452.6 1648.58
#Mann= 3 ,-1 , 0
       0     .04       0   176.6    .045       0   212.3      .1       0
Bank Sta=176.6,212.3
XS Rating Curve= 0 ,0
Exp/Cntr=0.3,0.1

Type RM Length L Ch R = 1 ,4002    ,190.1,196.9,199.2
XS GIS Cut Line= 2
2020675.07929496220090.0237779822020873.03244083219702.308854124
#Sta/Elev= 30
       0 1692.57    31.3 1674.34    38.7 1667.93    43.4 1664.98      58  1659.9
    62.9 1654.82    79.2 1629.88    82.4 1628.74    95.9 1628.83   101.9 1627.51
   172.6  1570.2   184.8  1564.9   200.8 1564.09   206.8 1562.68   211.8 1561.26
   230.2 1559.95   240.2 1560.79     245  1563.2   252.3 1569.41   260.4  1578.8
     265 1581.45   267.1 1582.13   285.5 1579.17   340.7 1598.28   373.9 1602.27
   387.2 1608.11     396  1615.3     407 1622.08   421.8 1627.17   435.3 1629.83
#Mann= 5 ,-1 , 0
       0      .1       0      50     .04       0     160      .1       0
   206.8    .045       0     245      .1       0
Bank Sta=206.8,245
XS Rating Curve= 0 ,0
Exp/Cntr=0.3,0.1

Type RM Length L Ch R = 1 ,3805    ,175.5,168.9,154.5
XS GIS Cut Line= 3
2020830.35553307 220146.821575982021010.62531569 219898.64891241
2021004.83672578219752.100755805
#Sta/Elev= 30
       0 1670.09     7.3 1660.31    18.2 1649.57    22.1 1642.47    27.6 1628.23
    32.3 1622.28    38.8 1617.07    44.1 1614.82    98.1  1613.6   104.7 1611.78
   112.8 1605.43     131  1585.5   133.7 1581.79   145.2 1560.95   156.8 1555.91
   170.9 1554.38   193.9 1556.15   217.9 1558.93   242.5 1555.42   254.7 1557.41
   269.6 1562.39   295.6 1575.32   307.3 1577.82     323  1578.7   343.4 1581.86
   392.8 1597.39   418.9 1604.04   428.8 1608.47   447.5 1621.52   453.4 1624.35
#Mann= 4 ,-1 , 0
       0     .04       0     130      .1       0   156.8    .045       0
   193.9      .1       0
#XS Ineff= 2 , 0
                             214            1565
Permanent Ineff=
       F       F
Bank Sta=156.8,193.9
XS Rating Curve= 0 ,0
Exp/Cntr=0.3,0.1

Type RM Length L Ch R = 1 ,3636    ,247.8,227.1,204.6
XS GIS Cut Line= 3
 2021039.4116241220230.1804460422021114.85972799219953.225111837
2021070.80859827219758.813424236
#Sta/Elev= 30
       0  1596.7    41.5 1596.47    49.3 1594.59    75.6  1583.2      96 1582.73
   106.2  1577.8   116.1 1567.73   133.4 1553.95   143.6 1551.82   167.4 1550.07
   174.2 1548.22   194.6  1545.6   208.2 1547.96     223 1553.61   262.6 1555.65
   275.6  1562.5   281.8 1564.29   299.6 1564.49   316.7 1568.13   340.2 1570.98
   363.8  1578.9   380.6 1581.99   414.2  1591.5   437.8 1595.67   457.9 1602.26
   461.4 1604.62   464.7 1608.63     468 1615.11   471.4 1617.73   486.4 1621.11
#Mann= 4 ,-1 , 0
       0     .06       0      90      .1       0   174.2    .045       0
   208.2      .1       0
#XS Ineff= 2 , 0
           155.5    1555
Permanent Ineff=
       F       F
Bank Sta=174.2,208.2
XS Rating Curve= 0 ,0
Exp/Cntr=0.3,0.1

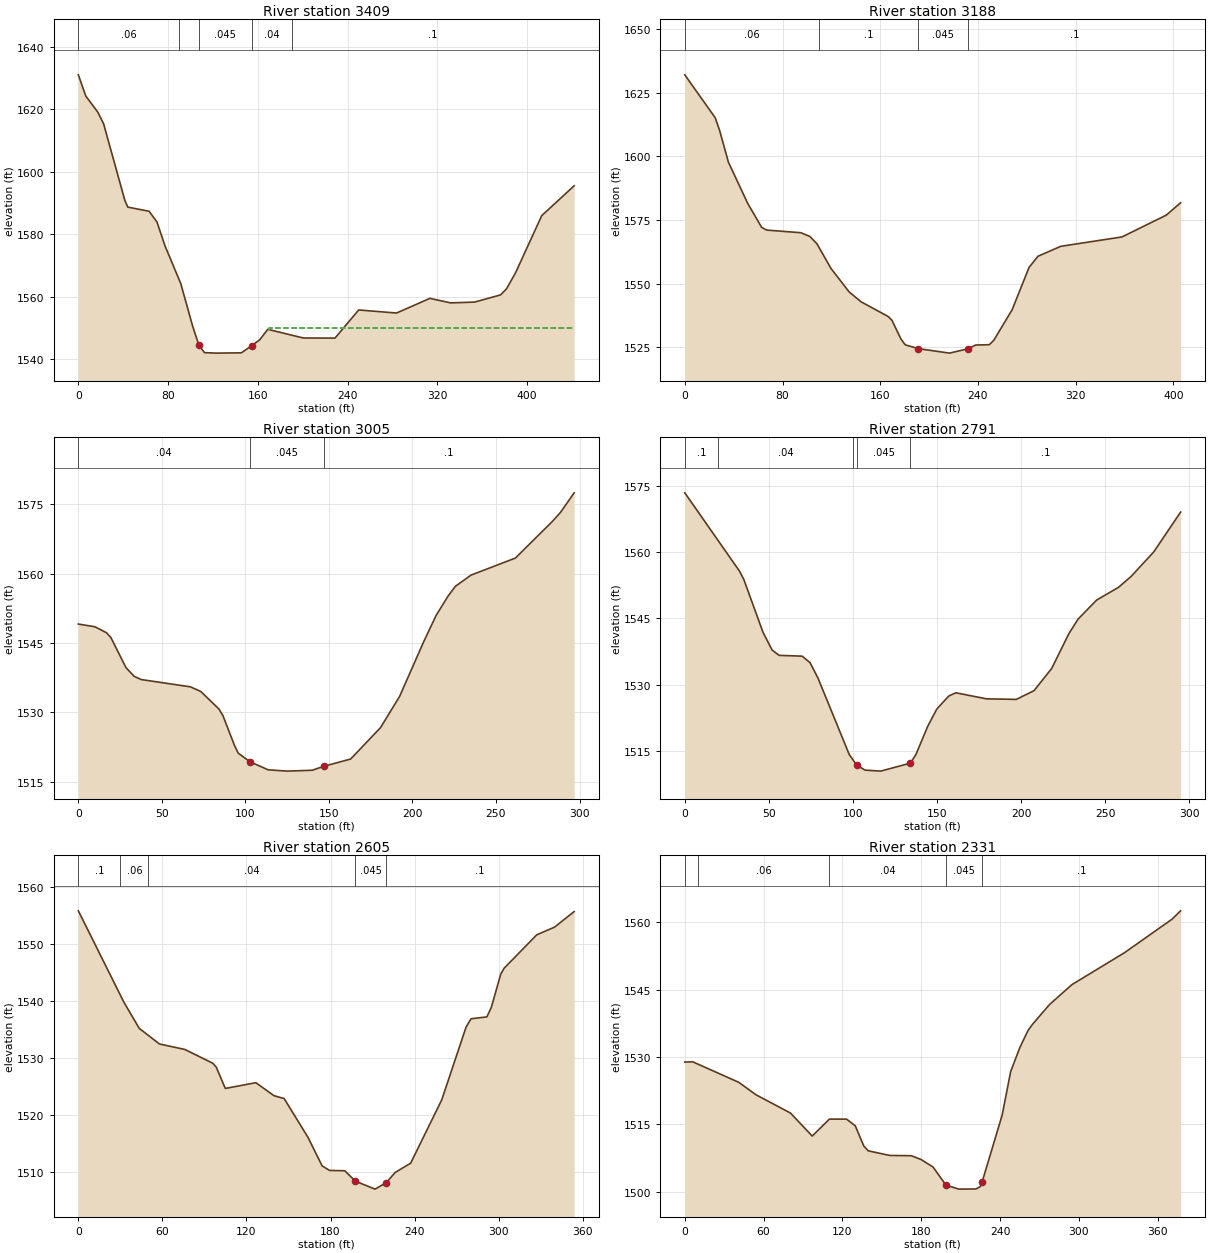
Type RM Length L Ch R = 1 ,3409    ,218.9,221.2,212.8
XS GIS Cut Line= 3
2021346.93738384220222.5975611952021252.69933752219981.929043007
2021226.50832164  219800.4951251
#Sta/Elev= 30
       0 1631.08     6.7 1624.26    17.3 1619.18    22.5 1615.44    41.5 1590.84
    44.1 1588.75    63.1 1587.42    70.1 1583.96    77.2 1576.38    91.3 1564.26
   101.9 1550.62   107.4 1544.59   112.4 1542.19     123 1542.03   145.3 1542.13
   154.7 1544.47   161.7 1546.31   168.8 1549.65   200.5 1546.87   228.7 1546.84
   249.8 1555.84   283.5 1554.86   313.3 1559.55   331.8  1558.1   353.1 1558.36
   376.3 1560.67   381.6 1562.64   389.6 1567.75   412.9 1586.02   441.8 1595.58
#Mann= 5 ,-1 , 0
       0     .06       0      90     .04       0   107.4    .045       0
   154.7     .04       0     190      .1       0
#XS Ineff= 2 , 0
                             170            1550
Permanent Ineff=
       F       F
Bank Sta=107.4,154.7
XS Rating Curve= 0 ,0
Exp/Cntr=0.3,0.1

Type RM Length L Ch R = 1 ,3188    ,196.1,182.9,172.5
XS GIS Cut Line= 2
2021540.92207014220147.0086829792021369.48791861 219779.10681471
#Sta/Elev= 30
       0 1632.01    24.9 1615.14    28.5 1610.15    35.7 1597.71    51.4 1581.59
    62.9 1572.08      67    1571      95 1569.97   102.4  1568.5   108.1 1565.67
   119.7 1555.92   134.5 1546.72   144.3 1542.82   166.6 1537.01   169.6 1535.52
   176.9 1528.24   180.5  1525.9   191.3 1524.41   216.7 1522.65   232.1 1524.39
   238.2 1525.84   249.3 1525.96   252.9 1527.68   267.9 1539.62   281.8  1556.3
   289.1 1560.71   307.8 1564.62   357.9 1568.31   394.1 1576.85   405.9 1581.74
#Mann= 4 ,-1 , 0
       0     .06       0     110      .1       0   191.3    .045       0
   232.1      .1       0
Bank Sta=191.3,232.1
XS Rating Curve= 0 ,0
Exp/Cntr=0.3,0.1

Type RM Length L Ch R = 1 ,3005    ,212.8,213.8,209.4
XS GIS Cut Line= 2
2021684.38452613219924.1557756242021467.19185309219721.907037077
#Sta/Elev= 30
       0  1549.1      10  1548.5    16.9 1547.21    19.5 1546.16    28.5 1539.68
    33.4 1537.78    37.8 1537.07    67.1  1535.5    73.3  1534.5    84.2 1530.69
    86.6 1529.23    93.5 1522.79    95.7 1521.15   102.8 1519.26   113.6 1517.54
   124.9 1517.25     140 1517.44   146.9 1518.29     163 1519.87   180.9 1526.67
   192.3 1533.41   206.7 1545.24   214.2 1550.98   221.2 1555.08   225.7 1557.27
   235.1  1559.7   261.6 1563.38   283.8 1571.33   288.6 1573.27   296.8 1577.51
#Mann= 3 ,-1 , 0
       0     .04       0   102.8    .045       0   146.9      .1       0
Bank Sta=102.8,146.9
XS Rating Curve= 0 ,0
Exp/Cntr=0.3,0.1

Type RM Length L Ch R = 1 ,2791    ,191.1,186.5,179.9
XS GIS Cut Line= 2
2021822.16123161219762.181476488 2021592.0084163 219577.82215223
#Sta/Elev= 30
       0 1573.37    32.5 1555.71    35.1 1553.81    46.5 1541.89    51.9 1537.89
    56.1 1536.67    69.8 1536.49    74.5 1535.02    79.2 1531.55    97.8 1514.29
   102.3 1511.87   107.2 1510.76   116.5 1510.53   134.2 1512.34   137.5 1514.31
   144.5 1520.66   149.9 1524.55     157 1527.49   161.2 1528.22   179.5 1526.85
   197.2 1526.73   207.7  1528.7   218.2  1533.7   228.4 1541.55   233.9 1544.85
   244.9 1549.14   257.9 1552.02   265.4 1554.47   278.9 1560.02   294.9 1569.03
#Mann= 5 ,-1 , 0
       0      .1       0      20     .04       0     100      .1       0
   102.3    .045       0   134.2      .1       0
Bank Sta=102.3,134.2
XS Rating Curve= 0 ,0
Exp/Cntr=0.3,0.1

Type RM Length L Ch R = 1 ,2605    ,248.8,273.7,301.1
XS GIS Cut Line= 3
2021961.45110058219681.6513388272021911.26411053219572.859574457
2021698.37835078219475.617432174
#Sta/Elev= 30
       0 1555.87    32.6 1539.76    43.5 1535.19    57.9 1532.45      76 1531.49
      96 1529.06    98.5 1528.35   104.9 1524.63   126.7 1525.64   139.7 1523.35
   146.9 1522.85   163.9 1516.04     174 1511.01   179.3 1510.21   190.2 1510.15
   197.7 1508.32   211.8 1506.92   219.8 1508.07   226.2 1509.86   237.2 1511.48
   259.4 1522.63   276.7 1535.38   280.3 1536.89   291.6 1537.21   294.8  1538.9
   301.5 1544.74   303.9 1545.77   327.2 1551.65   339.9    1553   353.9 1555.74
#Mann= 5 ,-1 , 0
       0      .1       0      30     .06       0      50     .04       0
   197.7    .045       0   219.8      .1       0
Bank Sta=197.7,219.8
XS Rating Curve= 0 ,0
Exp/Cntr=0.3,0.1

Type RM Length L Ch R = 1 ,2331    ,148.9,145.7,142.9
XS GIS Cut Line= 3
 2022045.8350709219656.9574823342022062.60227532219374.080414289
2022031.69535209219285.213875602
#Sta/Elev= 30
       0 1528.91     6.1 1528.95    41.1 1524.39    54.2 1521.62    80.5 1517.54
      97 1512.42   110.1  1516.2   123.2 1516.19   129.8  1514.7   136.3 1510.19
   139.7 1509.13   156.1  1508.1   172.5 1508.04   179.9 1507.19     189 1505.53
   198.8  1501.5   208.7  1500.6   221.8 1500.64   225.1  1501.2   226.4 1502.22
   241.6 1517.06   248.1 1526.76   255.1 1532.14   261.3 1535.93   264.6 1537.27
   277.7 1541.72   294.8 1546.16   334.8 1553.27   370.8 1560.69   377.5 1562.59
#Mann= 5 ,-1 , 0
       0      .1       0      10     .06       0     110     .04       0
   198.8    .045       0   226.4      .1       0
Bank Sta=198.8,226.4
XS Rating Curve= 0 ,0
Exp/Cntr=0.3,0.1

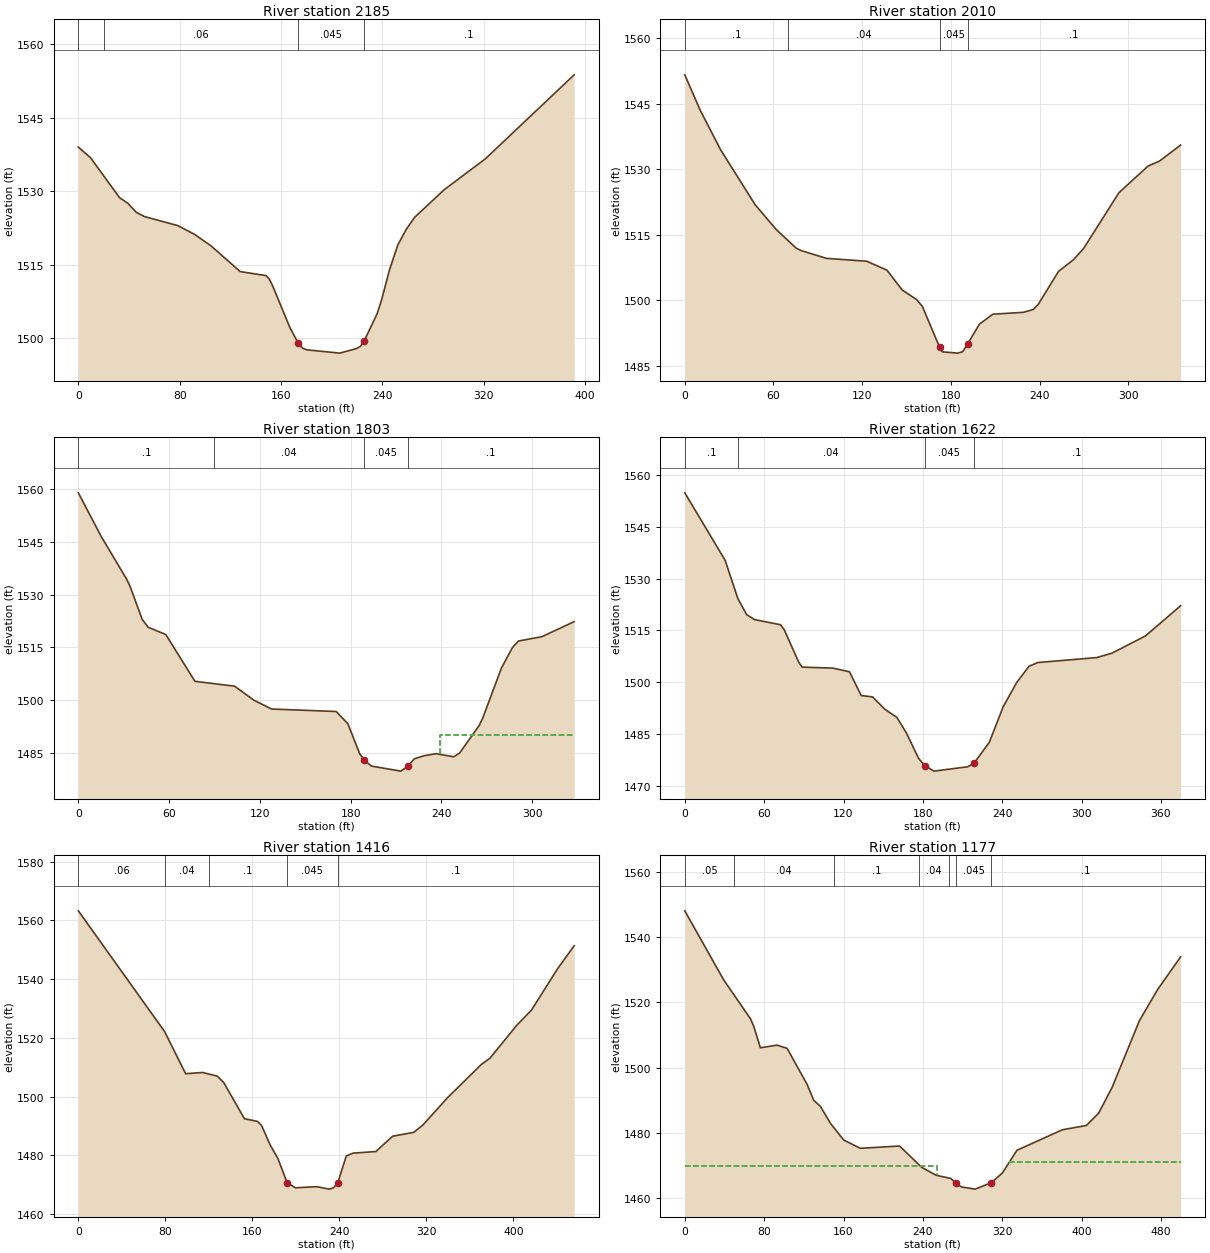
Type RM Length L Ch R = 1 ,2185    ,184.1,175.3,167.9
XS GIS Cut Line= 3
2022198.67512641 219668.232426852022202.88143756219385.015721885
2022158.14177432219286.370787579
#Sta/Elev= 30
       0 1539.04     9.6 1536.88    32.6 1528.71    39.2 1527.55    45.7 1525.73
    52.3 1524.85    78.5 1523.02    91.7 1521.24   104.8 1518.88   127.8 1513.63
   148.2 1512.81   150.7 1512.16   153.4 1510.76   167.1  1502.2   173.7    1499
     177 1498.01   180.5 1497.65   206.5 1496.98   219.6  1497.9   222.9 1498.39
   225.8  1499.5     236 1505.01   239.3 1507.65   245.9  1514.1   252.4  1519.1
     259 1522.25   265.6  1524.7   289.1 1530.37   321.5 1536.65   391.6 1553.79
#Mann= 4 ,-1 , 0
       0      .1       0      20     .06       0   173.7    .045       0
   225.8      .1       0
Bank Sta=173.7,225.8
XS Rating Curve= 0 ,0
Exp/Cntr=0.3,0.1

Type RM Length L Ch R = 1 ,2010    ,213.6,207.1,201.2
XS GIS Cut Line= 2
2022424.61674387219622.8112812512022332.65702251219300.310128415
#Sta/Elev= 30
       0 1551.63    10.5 1543.47    24.2 1534.48    47.5 1521.92    61.7 1516.25
    75.4 1511.91    78.8 1511.36    95.8 1509.59   123.1 1508.93   136.8 1506.87
     147 1502.36   156.8 1500.15   160.7 1498.59   172.4 1489.19   174.3 1488.17
   184.5 1487.88     188  1488.2   191.4 1490.04   199.3 1494.52   208.4  1496.8
   228.9 1497.22   235.7 1497.87   239.2 1499.11   252.8  1506.6     263 1509.31
   269.8 1511.87   293.7 1524.64   313.4 1530.74     321 1531.85   335.4 1535.54
#Mann= 4 ,-1 , 0
       0      .1       0      70     .04       0   172.4    .045       0
   191.4      .1       0
Bank Sta=172.4,191.4
XS Rating Curve= 0 ,0
Exp/Cntr=0.3,0.1

Type RM Length L Ch R = 1 ,1803    ,187.6,181.1,176.9
XS GIS Cut Line= 2
2022669.37529582 219530.196564512022493.68155064219253.444730003
#Sta/Elev= 30
       0 1558.86    15.3 1546.33    31.9 1534.39    34.3 1532.23    42.2 1522.95
    46.2  1520.7    57.8 1518.65    77.1 1505.36   103.3 1503.98   116.1    1500
   127.7  1497.5   170.5 1496.79   178.2 1493.31     186 1484.83   188.8 1483.09
   193.8  1481.3   213.2 1479.87   217.8 1481.21   222.1 1483.37   228.7 1484.25
   236.5 1484.81   248.2 1483.94   252.1 1485.02   264.9 1492.75   267.3 1494.85
   279.7 1509.11     287 1514.93     291  1516.8   306.5 1518.03   327.8  1522.3
#Mann= 4 ,-1 , 0
       0      .1       0      90     .04       0   188.8    .045       0
   217.8      .1       0
#XS Ineff= 2 , 0
                             239            1490
Permanent Ineff=
       F       F
Bank Sta=188.8,217.8
XS Rating Curve= 0 ,0
Exp/Cntr=0.3,0.1

Type RM Length L Ch R = 1 ,1622    ,195.2,205.2,208.1
XS GIS Cut Line= 2
2022852.32191861219411.9033282752022597.32858109219137.121853094
#Sta/Elev= 30
       0 1554.81    30.5 1535.29    40.2 1524.14    46.8 1519.57    52.8 1518.13
    72.3 1516.66    75.2  1515.2    86.2 1505.78    88.7 1504.39   111.8 1504.11
   124.5 1503.06   133.4 1496.17     142 1495.78   151.2 1492.22   160.3 1489.87
   167.5 1485.39   176.8 1477.99   181.4 1475.91   188.4 1474.31   213.9 1475.57
   218.5 1476.52   230.2 1482.61   240.8 1492.98   251.1 1500.03   260.3 1504.65
   266.9 1505.72   311.4 1507.15     323 1508.43   348.3 1513.41   374.9 1522.15
#Mann= 4 ,-1 , 0
       0      .1       0      40     .04       0   181.4    .045       0
   218.5      .1       0
Bank Sta=181.4,218.5
XS Rating Curve= 0 ,0
Exp/Cntr=0.3,0.1

Type RM Length L Ch R = 1 ,1416    ,241.5,239.5,229.1
XS GIS Cut Line= 2
2022988.57847496219328.5529169622022744.23867061218943.493853557
#Sta/Elev= 30
       0 1563.23    79.3 1522.18    98.7 1507.81   114.2 1508.23   127.8 1506.99
   133.7 1504.82   152.8 1492.49   164.8 1491.59   168.6 1490.15   176.4 1483.58
   183.7 1478.83     192 1470.74   199.7 1468.99   219.2 1469.37   230.8 1468.54
   234.7 1468.99   238.6 1470.68   246.4 1479.79   252.6 1480.78   273.6 1481.33
   289.1 1486.54   308.5 1487.87   316.8 1490.32   339.6 1499.67   370.7 1510.99
   378.5 1513.05   403.3 1524.33   416.7 1529.43   440.6 1543.44     456 1551.35
#Mann= 5 ,-1 , 0
       0     .06       0      80     .04       0     120      .1       0
     192    .045       0   238.6      .1       0
Bank Sta=192,238.6
XS Rating Curve= 0 ,0
Exp/Cntr(USF)=0,0
Exp/Cntr=0.5,0.3

Type RM Length L Ch R = 1 ,1177    ,99.7,97.4,88.5
XS GIS Cut Line= 3
2023108.33650106 219303.209291662023150.87324149219111.820060564
2022933.01767671218900.158724739
#Sta/Elev= 30
       0    1548    39.2 1526.85    66.1 1514.98    69.5 1512.64    76.2 1506.06
      93 1506.87   103.1 1505.89   123.3 1494.85     130 1489.95   136.7 1488.12
   146.8 1482.93   160.2  1477.8     177 1475.27   216.5 1475.98   238.8 1469.43
   253.3 1467.03   268.3 1466.02     273 1464.64   278.8 1463.44   292.8 1462.77
     309 1464.75   320.1  1467.7   334.8 1474.66   380.6 1480.95   404.8 1482.26
   417.2 1486.04   430.9 1494.04   458.3 1514.38   476.6 1523.89   499.8  1533.9
#Mann= 7 ,-1 , 0
       0     .05       0      50     .04       0     150      .1       0
  236.06     .04       0  266.06      .1       0     273    .045       0
     309      .1       0
#XS Ineff= 2 , 0
             254  1469.8     327          1471.2
Permanent Ineff=
       F       F
Bank Sta=273,309
XS Rating Curve= 0 ,0
Exp/Cntr(USF)=0,0
Exp/Cntr=0.5,0.3

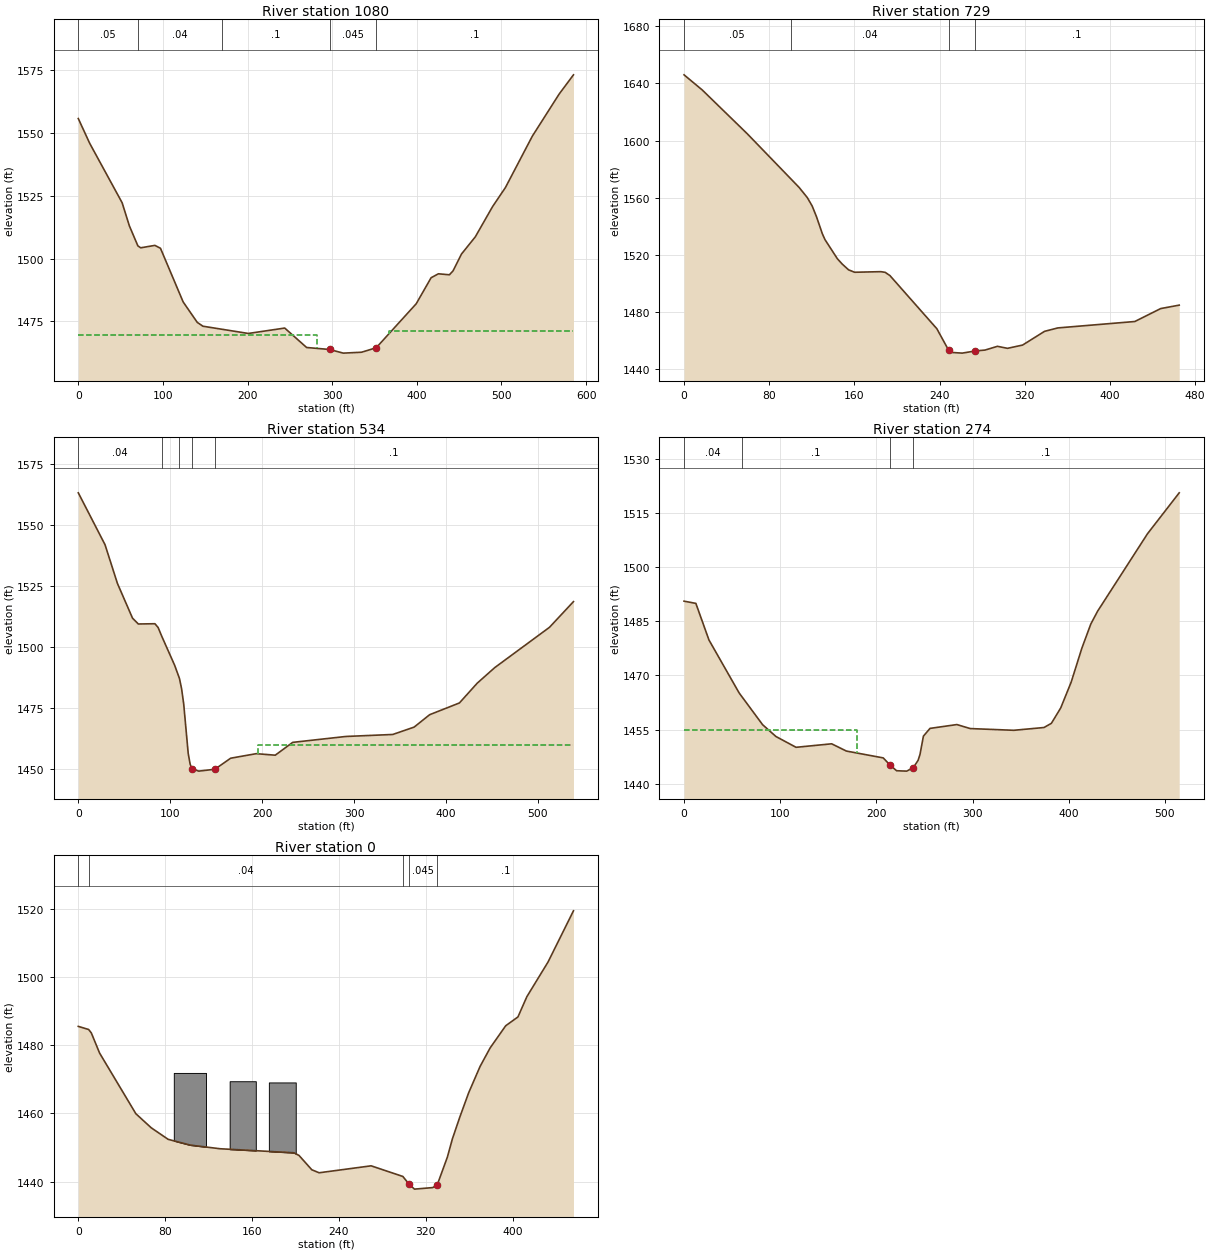
Type RM Length L Ch R = 1 ,1080    ,317.3,350.2,407.1
XS GIS Cut Line= 3
2023187.34814549 219327.347939472023232.73681347219100.536396262
2023002.21174652218832.173284966
#Sta/Elev= 30
       0 1555.71    13.5 1545.84    51.8 1522.22    60.3 1513.08    70.4 1505.07
    73.7  1504.3    90.5 1505.26    97.1 1504.12   123.9 1482.77   140.6 1474.63
   147.3 1473.11   200.9 1470.23   243.9 1472.38   269.8 1464.65   296.9 1463.86
   313.1 1462.41   334.7 1462.77     352 1464.54   399.3 1482.05   416.9  1492.4
   425.5 1493.96   438.5 1493.57   442.8 1495.12   452.8 1501.83   469.1 1508.66
   489.5 1520.68   504.7 1528.27   536.5 1548.71   568.2 1565.46   585.1  1573.1
#Mann= 5 ,-1 , 0
       0     .05       0      70     .04       0     170      .1       0
   296.9    .045       0     352      .1       0
#XS Ineff= 2 ,-1
       0   281.9  1469.8     367585.0889  1471.2
Permanent Ineff=
       F       F
Bank Sta=296.9,352
XS Rating Curve= 0 ,0
Exp/Cntr(USF)=0,0
Exp/Cntr=0.5,0.3

Type RM Length L Ch R = 1 ,729     ,192.3,195.7,198
XS GIS Cut Line= 2
2023266.17919509219487.1818998932023537.89566265219109.674919305
#Sta/Elev= 30
       0 1646.04    17.1 1635.44    59.4 1604.81   108.1 1567.28   115.8 1560.15
   120.3 1554.36   124.3 1547.03   129.9 1534.89   132.4 1530.76     144 1517.45
   148.7  1513.6   154.5 1509.67   160.2 1507.97   184.9 1508.38     189 1507.88
   193.4 1505.63   237.5 1468.43   248.6  1453.3     250 1451.95   261.2 1451.41
   273.3 1452.89   282.7 1453.55   294.4 1456.17   303.8 1454.76     318 1457.05
   338.6 1466.64   351.1 1469.04   423.4 1473.52   447.7 1482.57   465.1 1484.97
#Mann= 4 ,-1 , 0
       0     .05       0     100     .04       0   248.6    .045       0
   273.3      .1       0
Bank Sta=248.6,273.3
XS Rating Curve= 0 ,0
Exp/Cntr(USF)=0,0
Exp/Cntr=0.3,0.1

Type RM Length L Ch R = 1 ,534     ,267.4,259.7,248.6
XS GIS Cut Line= 3
2023444.95919512219518.8916033782023717.69781105219232.257510475
2023840.29504652219158.455194596
#Sta/Elev= 30
       0 1563.37    29.1 1542.07    42.6 1526.18      59 1511.95    65.3 1509.55
    83.4 1509.66    86.9 1508.08    90.6  1504.7   104.8 1492.65   110.1 1487.17
   112.4 1482.98   114.7 1476.72   119.6 1456.43   121.7 1452.03   123.61450.225
     131 1449.18   148.61449.945   165.8 1454.48   193.6 1456.34   214.3 1455.72
   233.3 1460.98   291.1  1463.4   342.2 1464.22   365.4 1467.24   382.3 1472.33
   414.7 1477.15   434.1 1485.28   453.2 1491.67   512.7 1508.19   538.8 1518.73
#Mann= 5 ,-1 , 0
       0     .04       0    90.6     .06       0   110.1      .1       0
   123.6    .045       0   148.6      .1       0
#XS Ineff= 2 , 0
                          195.64         1459.98
Permanent Ineff=
       F       F
Bank Sta=123.6,148.6
XS Rating Curve= 0 ,0
Exp/Cntr(USF)=0,0
Exp/Cntr=0.3,0.1

Type RM Length L Ch R = 1 ,274     ,263.1,273.9,287.4
XS GIS Cut Line= 2
2023699.79252227219709.2837370542023872.77769681219224.320933344
#Sta/Elev= 30
       0 1490.62    12.3    1490    25.9 1479.85    57.3 1465.15    81.7 1456.34
    95.6 1453.06   116.5 1450.07   153.5 1451.04   168.8 1449.03   207.1 1447.13
     214  1445.2     221 1443.57   231.5 1443.46   238.3  1444.4   243.4 1446.46
   245.4 1448.14   248.9 1453.17   255.8 1455.32   283.7 1456.38   297.6 1455.27
   342.9 1454.79   374.3 1455.56     382 1456.73   391.7    1461   402.6 1468.19
   413.6 1477.52     423 1484.29     430 1487.82   481.9 1509.32   514.9 1520.68
#Mann= 4 ,-1 , 0
       0     .04       0      60      .1       0     214    .045       0
   238.3      .1       0
#XS Ineff= 2 , 0
             180    1455
Permanent Ineff=
       F       F
Bank Sta=214,238.3
XS Rating Curve= 0 ,0
Exp/Cntr(USF)=0,0
Exp/Cntr=0.3,0.1

Type RM Length L Ch R = 1 ,0       ,183.2,183.4,186.6
XS GIS Cut Line= 3
2023756.85851061219796.5717061612024014.73181861219622.048639244
2024121.57705275219524.707260414
#Sta/Elev= 30
       0 1485.55     9.5 1484.64      12 1483.62    19.6 1477.72      53 1459.91
    67.2 1455.77    82.7  1452.4   102.8 1450.72   130.6 1449.63   198.5 1448.45
   203.2 1447.67     215 1443.46   221.7 1442.58   269.6 1444.62   298.8  1441.5
   304.7 1439.18   309.5 1437.78   326.3 1438.23   330.5 1439.06   339.8 1447.17
   344.4 1452.51   351.4 1459.05   359.4 1466.05   369.9 1473.78   379.2 1479.24
   393.5 1485.73   404.8 1488.33     413 1494.28   432.5 1504.45   455.9 1519.47
#Mann= 5 ,-1 , 0
       0    .016       0     9.5     .04       0   298.8      .1       0
   304.7    .045       0   330.5      .1       0
#Block Obstruct= 3 ,-1
   87.92  117.57 1471.89  139.35  163.42 1469.45  175.45   200.2  1469.1
Bank Sta=304.7,330.5
XS Rating Curve= 0 ,0
Exp/Cntr(USF)=0,0
Exp/Cntr=0.3,0.1
LCMann Table=0

Chan Stop Cuts=-1
Use User Specified Reach Order=0
Composite Channel Slope=5